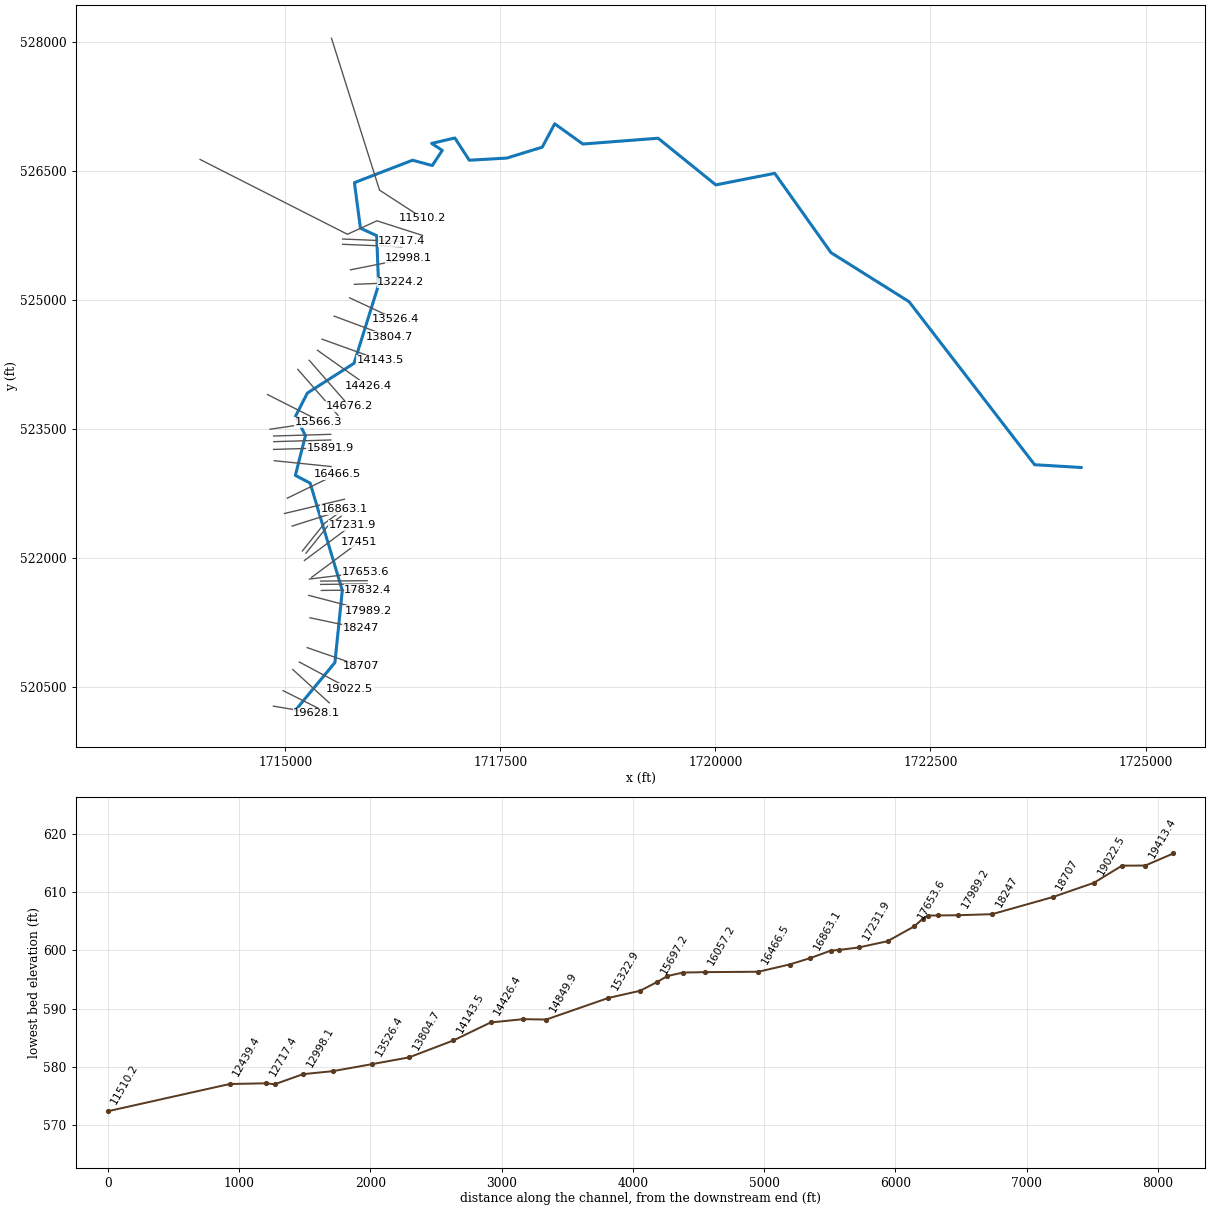
--- ScaryCr.prj (project) ---

Proj Title=ScaryCr
Current Plan=p01
Default Exp/Contr=0,0
English Units
Geom File=g01
Flow File=f01
Plan File=p01
BEGIN DESCRIPTION:
AMEC Environment & Infrastructure, 2013
Projection: NAD 1983 State Plane West Virginia South FIPS 4702 (US Feet)
Vertical Datum: NAVD 1988
END DESCRIPTION:
DSS Export Rating Curves= 0
DSS Export Rating Curve Sorted= 0
DSS Export Volume Flow Curves= 0
DXF OffsetX= 0
DXF OffsetY= 0
DXF ScaleX= 0
DXF ScaleY= 0

--- ScaryCr.p01 (plan) ---

Plan Title=Floodplain
Program Version=4.00
Geom File=g01
Flow File=f01
K Sum by GR=0
Std Step Tol=0.01
Critical Tol=0.01
Num of Std Step Trials=20
Max Error Tol=0.3
Flow Tol Ratio=0.001
Split Flow NTrial=30
Split Flow Tol=0.02
Split Flow Ratio=0.02
Log Output Level=0
Friction Slope Method=1
Unsteady Friction Slope Method=2
Unsteady Bridges Friction Slope Method=1
Global Log Level=0
CheckData=False
Run HTab=0
Run UNet=0
Run PostProcess=0
UNET Theta=0
UNET Theta Warmup=0
UNET ZTol=0
UNET ZSATol=0
UNET MxIter=0
UNET MaxInSteps=0
UNET DtIC=0
UNET DtMin=0
UNET MaxCRTS=0
UNET WFStab=0
UNET SFStab=0
UNET WFX=0
UNET SFX=0
UNET DSS MLevel=0
UNET DZMax Abort=0
UNET Convert EG Bridges=0
UNET Use Existing IB Tables=0
UNET Froude Limit=0
UNET Froude Power=0
Write IC File=0
Echo Input=False
Echo Output=False
Write Detailed=0

--- ScaryCr.f01 (steady flow) ---

Flow Title=USGS Regress. Eqn. (2010) - Western-Plateaus
Program Version=4.10
Number of Profiles= 1
Profile Names=P100yr
River Rch & RM=ScaryCr,Main            ,19628.1
     755
River Rch & RM=ScaryCr,Main            ,19236.5
     960
River Rch & RM=ScaryCr,Main            ,19022.5
     963
River Rch & RM=ScaryCr,Main            ,18707
     965
River Rch & RM=ScaryCr,Main            ,18247
    1058
River Rch & RM=ScaryCr,Main            ,17231.9
    1088
River Rch & RM=ScaryCr,Main            ,15322.9
    1118
River Rch & RM=ScaryCr,Main            ,13804.7
    1168
River Rch & RM=ScaryCr,Main            ,12998.1
    1242
River Rch & RM=ScaryCr,Main            ,11510.2
    1265
River Rch & RM=ScaryCr,Main            ,11196.4
    1771
River Rch & RM=ScaryCr,Main            ,10157.8
    1775
River Rch & RM=ScaryCr,Main            ,9094.7
    1791
River Rch & RM=ScaryCr,Main            ,7309.7
    1856
River Rch & RM=ScaryCr,Main            ,6602.7
    2258
River Rch & RM=ScaryCr,Main            ,5229.2
    2341
River Rch & RM=ScaryCr,Main            ,2145.4
    2423
River Rch & RM=ScaryCr,Main            ,283.1
    2519
River Rch & RM=ScaryCr,Main            ,49
    2520
Boundary for River Rch & Prof#=ScaryCr,Main            , 1
Up Type= 0
Dn Type= 3
Dn Slope=0.0001
DSS Import GetInterval= 0
DSS Import GetPeak= 0
DSS Import FillOption= 0

--- ScaryCr.g01 (geometry) ---

Geom Title=USGS 3m DEM
Program Version=4.10

River Reach=ScaryCr         ,Main
Reach XY= 30
     1715117.558      520232.671     1715576.504      520787.588
     1715662.442      521626.129     1715288.744      522873.525
     1715116.869      522963.369     1715234.056      523425.609
     1715118.171      523650.869     1715256.192        523920.4
      1715799.16      524266.754     1716084.317      525178.213
     1716062.181      525749.827     1715873.379      525837.067
     1715803.238      526366.293     1716478.761      526627.026
     1716708.796      526565.394     1716824.247       526741.61
     1716700.983      526822.339     1716970.949      526885.707
     1717138.483      526627.026     1717575.115        526652.2
     1717986.574      526778.936     1718131.539      527050.637
     1718458.796      526815.394     1719333.188      526882.842
     1720004.412      526340.308     1720689.091      526474.856
     1721343.388      525552.547     1722250.506      524982.886
     1723710.358      523087.486     1724250.966      523055.295

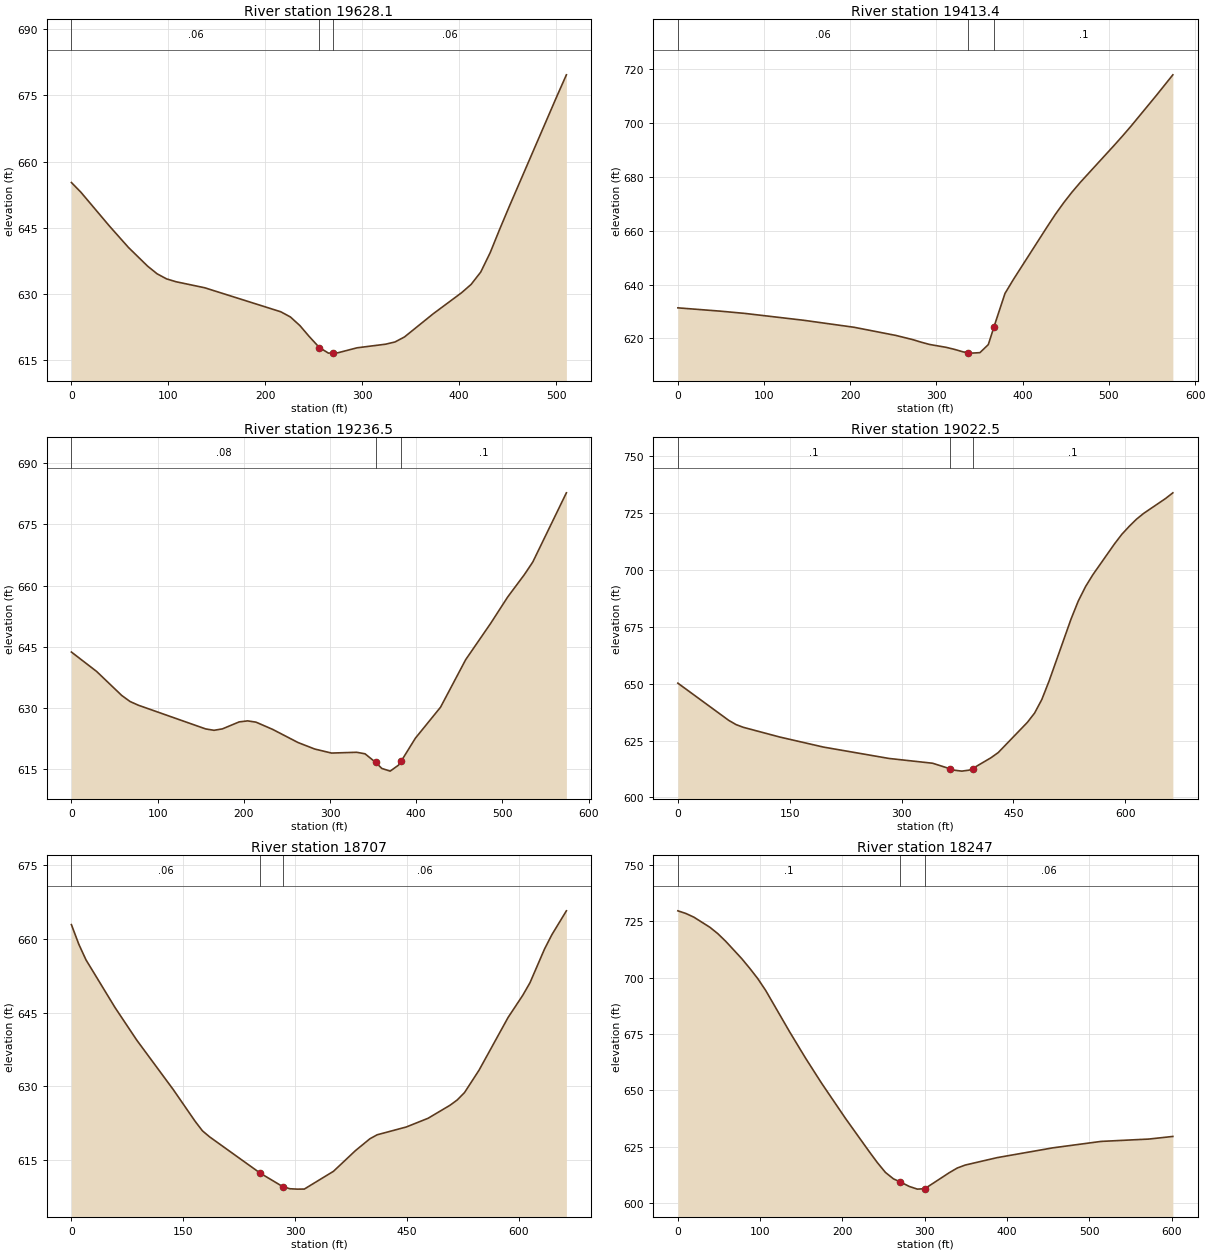
Type RM Length L Ch R = 1 ,19628.1 ,223.5,214.8,205.5
XS GIS Cut Line= 2
     1714861.456      520281.169     1715365.123      520196.962
#Sta/Elev= 30
       0  655.25     9.8  653.05    39.3  645.37    58.9  640.53    78.6  636.31
    88.4  634.57    98.2  633.42     108  632.77   137.5  631.41     216  625.97
   225.9   624.8   235.7  622.85   245.5  620.33   255.8 617.872   265.2   616.6
     270 616.639     275  616.68   294.6   617.8   324.1  618.62   333.9  619.13
   343.7  620.27   373.2   625.5   402.6  630.29   412.4  632.17   422.3  634.96
   432.1  639.37   441.9  644.68   451.7  649.79   500.8  674.75   510.7  679.65
#Mann= 3 , 0 , 0
       0     .06       0   255.8    .045       0     270     .06       0
Bank Sta=255.8,270
XS Rating Curve= 0 ,0
Exp/Cntr=0.3,0.1

Type RM Length L Ch R = 1 ,19413.4 ,185,176.9,168.8
XS GIS Cut Line= 2
     1714974.392      520460.773     1715488.063      520204.216
#Sta/Elev= 30
       0  631.35    48.7  630.14    77.8  629.28     146  626.73   204.4  624.13
     253  621.09   272.5  619.54   282.2  618.59     292  617.74   311.4  616.66
   321.2  615.89   330.9  614.98   336.5  614.71   340.6  614.52   350.4   614.7
   360.1  617.69   366.5  624.06   369.8  627.34   379.5  636.73   389.3  641.94
   428.2  661.39   437.9  666.11   447.7  670.49   457.4  674.45   467.1   678.1
     506  691.72   515.8  695.24   525.5  698.84   554.7  710.19   574.2  717.98
#Mann= 3 , 0 , 0
       0     .06       0   336.5    .045       0   366.5      .1       0
Bank Sta=336.5,366.5
XS Rating Curve= 0 ,0
Exp/Cntr=0.3,0.1

Type RM Length L Ch R = 1 ,19236.5 ,205.2,213.9,222.8
XS GIS Cut Line= 2
     1715087.065      520706.477     1715511.087      520319.327
#Sta/Elev= 30
       0   643.7    29.2  638.95    58.4  633.05    68.1  631.56    77.8  630.65
   155.7  624.85   165.4  624.51   175.2  624.86   194.6  626.57   204.4  626.82
   214.1  626.51   233.6  624.72   262.8  621.52   282.2  619.92   301.7  618.93
   330.9  619.12   340.6  618.75   352.9  616.65   360.1  615.16   369.8   614.5
   379.5  615.98   382.9  617.06     399  622.57   428.2  630.17   457.4  641.84
   486.6  650.81     506  657.17   525.5   662.7   535.2  665.77   574.2  682.74
#Mann= 3 , 0 , 0
       0     .08       0   352.9    .045       0   382.9      .1       0
Bank Sta=352.9,382.9
XS Rating Curve= 0 ,0
Exp/Cntr=0.3,0.1

Type RM Length L Ch R = 1 ,19022.5 ,313,315.6,270.3
XS GIS Cut Line= 2
     1715162.741       520793.87     1715748.589      520481.944
#Sta/Elev= 30
       0  650.26    68.3  633.87    78.1  632.02    87.8  630.83   136.6  626.56
   195.2  622.14     283  617.14   341.6  615.03   365.2  612.56   370.9  611.96
   380.7  611.56   390.4  611.99   395.2   612.7   419.7  617.42   429.5  619.71
   468.5  632.97   478.3   637.1     488  643.08   497.8  651.26   527.1  678.41
   536.8  686.34   546.6  692.74   556.4  697.96   585.6  711.61   595.4   715.8
   605.2  719.27   614.9   722.4   624.7     725     654  731.52   663.7  734.01
#Mann= 3 , 0 , 0
       0      .1       0   365.2    .045       0   395.2      .1       0
Bank Sta=365.2,395.2
XS Rating Curve= 0 ,0
Exp/Cntr=0.3,0.1

Type RM Length L Ch R = 1 ,18707   ,454.1,460,498.5
XS GIS Cut Line= 2
     1715254.344       520961.07     1715881.602       520744.13
#Sta/Elev= 30
       0  662.95     9.8     659    19.5  655.79    58.6  646.04    87.8   639.4
   136.6  629.36   165.9  622.91   175.7  620.97   185.4  619.73   253.4  612.33
   283.4  609.61   292.8  609.18   302.6   609.1   312.3  609.11   351.4  612.73
   380.7  616.92   400.2  619.35   409.9  620.16     449  621.75   478.3  623.53
   507.6  626.17   517.3  627.25   527.1  628.76   546.6  633.32   585.6  644.07
   605.2  648.56   614.9  651.13   634.4  657.99   644.2  660.89   663.7  665.76
#Mann= 3 , 0 , 0
       0     .06       0   253.4    .045       0   283.4     .06       0
Bank Sta=253.4,283.4
XS Rating Curve= 0 ,0
Exp/Cntr=0.3,0.1

Type RM Length L Ch R = 1 ,18247   ,261.4,257.8,251.4
XS GIS Cut Line= 2
      1715286.14      521308.317     1715874.617      521184.438
#Sta/Elev= 30
       0  729.57     9.7   728.4    19.4  726.77    38.8   722.3    48.5  719.46
    58.2  716.03    77.6  708.37    87.3  704.09      97  699.55   106.7  694.26
   135.8  675.91   155.2  664.22   174.6  653.15   203.7  637.51   232.8  622.66
   242.5  617.88   252.2  613.58   261.9  610.74     270  609.41   281.3  607.35
     291  606.18     300  606.37   329.8  613.48   339.5  615.55   349.2  616.86
     388  620.15   455.9   624.5   514.1  627.33   572.3  628.38   601.4  629.54
#Mann= 3 , 0 , 0
       0      .1       0     270    .045       0     300     .06       0
Bank Sta=270,300
XS Rating Curve= 0 ,0
Exp/Cntr=0.3,0.1

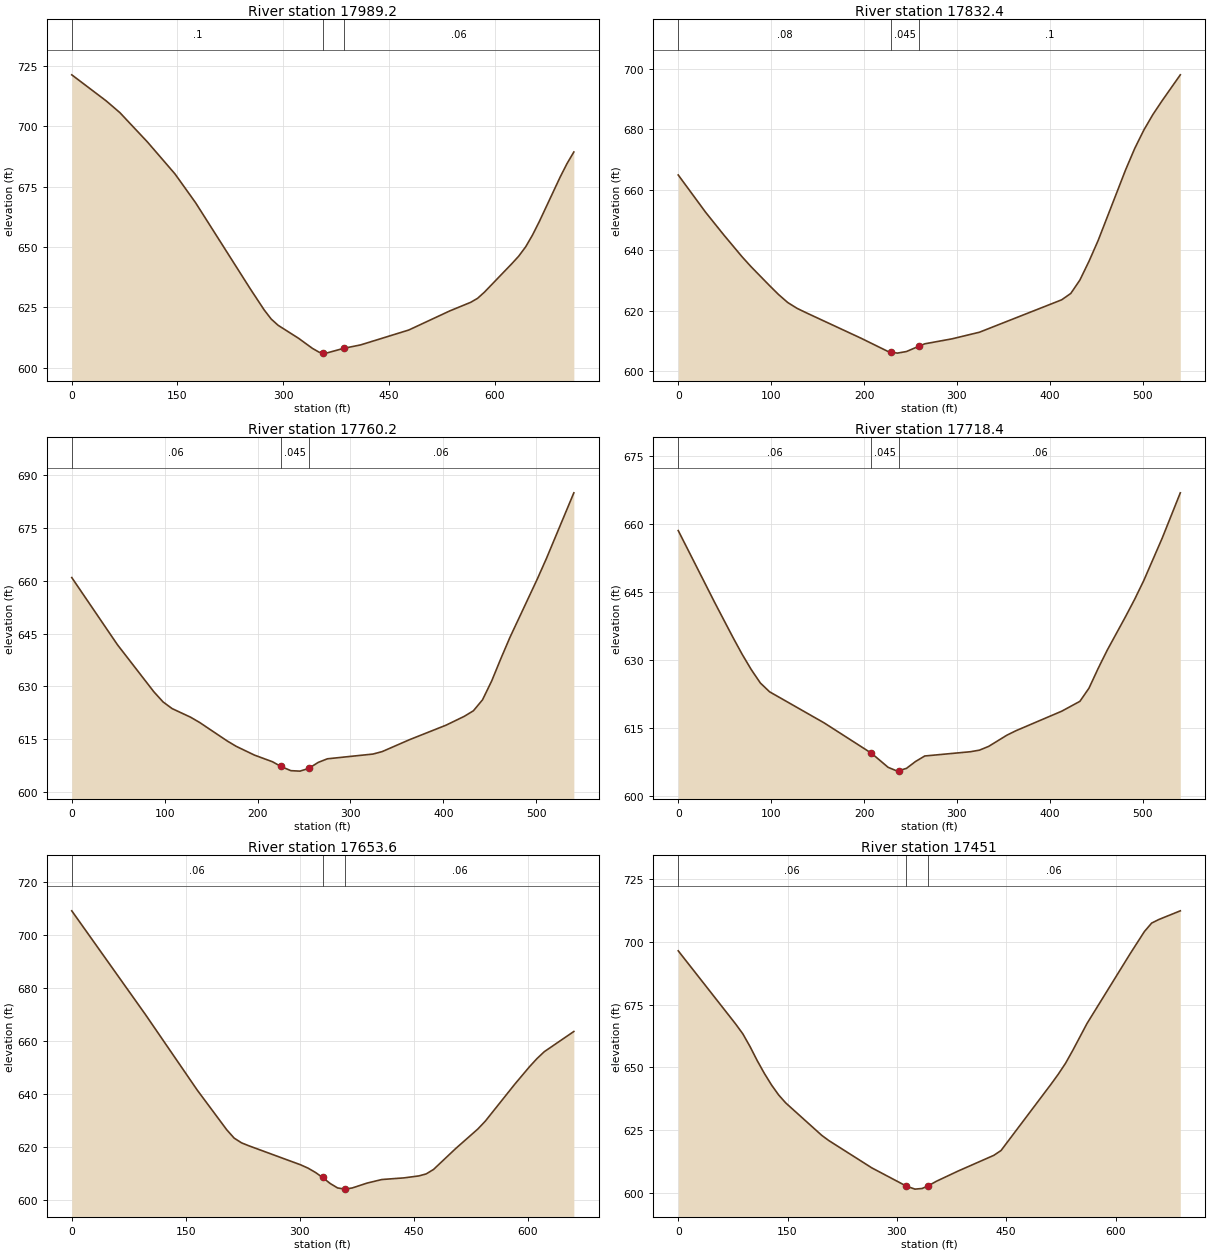
Type RM Length L Ch R = 1 ,17989.2 ,148.7,156.7,164.7
XS GIS Cut Line= 2
     1715272.728      521568.721     1715962.037      521388.856
#Sta/Elev= 30
       0  721.34    48.8  710.55    68.3  705.66   107.4   693.5   146.4  680.29
   175.7  668.33   253.7  632.46   273.2  623.83     283  620.12   292.8  617.53
     322  612.11   341.6  607.94   351.3  606.34   356.3  606.17   361.1     606
   386.3  608.02   409.9  609.41   478.2  615.58   536.7  623.54     566  627.05
   575.8  628.71   585.5  631.26   624.6  643.13   634.3  646.23   644.1  650.08
   653.8  654.97   663.6  660.65   692.9  678.92   702.6   684.5   712.4  689.36
#Mann= 3 , 0 , 0
       0      .1       0   356.3    .045       0   386.3     .06       0
Bank Sta=356.3,386.3
XS Rating Curve= 0 ,0
Exp/Cntr=0.3,0.1

Type RM Length L Ch R = 1 ,17832.4 ,72.8,72.3,71
XS GIS Cut Line= 2
     1715418.139      521626.132     1715958.645       521631.37
#Sta/Elev= 30
       0   664.9    29.5  652.56    49.1  645.05    68.8  637.81    78.6   634.5
    98.3   628.3   108.1  625.32   117.9   622.7   127.8   620.8   137.6  619.34
   196.6  610.92     226  606.48   229.2  606.31   235.9  605.96   245.7  606.49
   259.2  608.26   265.4  609.04   294.8  610.69   324.3  612.88   412.8   623.6
   422.6  625.71   432.4  630.14   442.2  636.35   452.1  643.27   481.6   666.6
   491.4  673.66   501.2  679.75     511  684.91   520.9  689.47   540.5  698.04
#Mann= 3 , 0 , 0
       0     .08       0   229.2    .045       0   259.2      .1       0
Bank Sta=229.2,259.2
XS Rating Curve= 0 ,0
Exp/Cntr=0.3,0.1

Type RM Length L Ch R = 1 ,17760.2 ,41.1,41.8,42.8
XS GIS Cut Line= 2
     1715410.637      521696.207     1715951.143      521701.445
#Sta/Elev= 30
       0  660.93    49.1  641.88    88.4  628.48    98.3   625.6   108.1   623.7
   127.8  621.28   137.6  619.78   167.1  614.56   176.9  613.01   196.6  610.51
   216.2   608.6     225   607.3   235.9  606.08   245.7  605.95     255  606.72
   265.4  608.44   275.2  609.45   324.3   610.8   334.2   611.5   363.6  614.88
   402.9     619   422.6  621.52   432.4   623.1   442.2  626.21   452.1  631.59
   461.9  637.89   471.7  643.94   501.2  660.54     511  666.36   540.5     685
#Mann= 3 , 0 , 0
       0     .06       0     225    .045       0     255     .06       0
Bank Sta=225,255
XS Rating Curve= 0 ,0
Exp/Cntr=0.3,0.1

Type RM Length L Ch R = 1 ,17718.4 ,61.4,64.8,68.4
XS GIS Cut Line= 2
     1715411.305      521734.487     1715951.811      521739.725
#Sta/Elev= 30
       0  658.47    39.3  642.58      59  634.86    68.8  631.18    78.6   627.8
    88.4  624.84    98.3   622.9   157.2  616.02     208  609.34     226  606.22
   235.9  605.39     238  605.52   245.7     606   255.5  607.52   265.4  608.73
   314.5  609.67   324.3  610.02   334.2  610.85   353.8  613.32   363.6  614.31
   412.8  618.61   432.4  620.79   442.2   623.7   452.1  628.07   461.9  632.11
   481.6   639.5   491.4  643.33   501.2  647.46   520.9  656.75   540.5   666.8
#Mann= 3 , 0 , 0
       0     .06       0     208    .045       0     238     .06       0
Bank Sta=208,238
XS Rating Curve= 0 ,0
Exp/Cntr=0.3,0.1

Type RM Length L Ch R = 1 ,17653.6 ,185.5,202.6,219.1
XS GIS Cut Line= 2
     1715279.275      521758.175     1715935.261      521838.543
#Sta/Elev= 30
       0  709.22    97.2  669.95   165.2  641.49   204.1  626.47   213.8  623.35
   223.5  621.57   233.3  620.44   301.3  613.27     311  612.02   320.7  610.41
   330.2  608.49   340.2  606.21   349.9  604.54   359.6  604.09   360.2  604.12
   369.3  604.54   388.8  606.38   408.2  607.72   437.4  608.34   456.8  609.08
   466.5  609.83   476.2  611.52   505.4  619.43   534.5  626.79   544.3  629.75
   583.1  643.71   602.6  650.35   612.3  653.38     622  656.01   660.9  663.64
#Mann= 3 , 0 , 0
       0     .06       0   330.2    .045       0   360.2     .06       0
Bank Sta=330.2,360.2
XS Rating Curve= 0 ,0
Exp/Cntr=0.3,0.1

Type RM Length L Ch R = 1 ,17451   ,218.1,219,218.7
XS GIS Cut Line= 2
     1715305.738      521778.173     1715858.295      522189.659
#Sta/Elev= 30
       0  696.43    78.7  667.33    88.6  663.39    98.4  658.38   108.3  652.76
   118.1  647.67     128  643.02   137.8  639.04   147.6  635.84   196.8  622.99
   206.7  620.87   265.7     610   312.8  602.78   324.8  601.55   334.6   601.8
   342.8  602.84   354.3  604.69   383.8  608.72     433     615   442.9  616.92
   511.8  643.44   521.6  647.37   531.5   651.7   541.3  656.77     561  667.56
     620  695.24   639.7  704.14   649.6  707.48   659.4   708.9   688.9  712.36
#Mann= 3 , 0 , 0
       0     .06       0   312.8    .045       0   342.8     .06       0
Bank Sta=312.8,342.8
XS Rating Curve= 0 ,0
Exp/Cntr=0.3,0.1

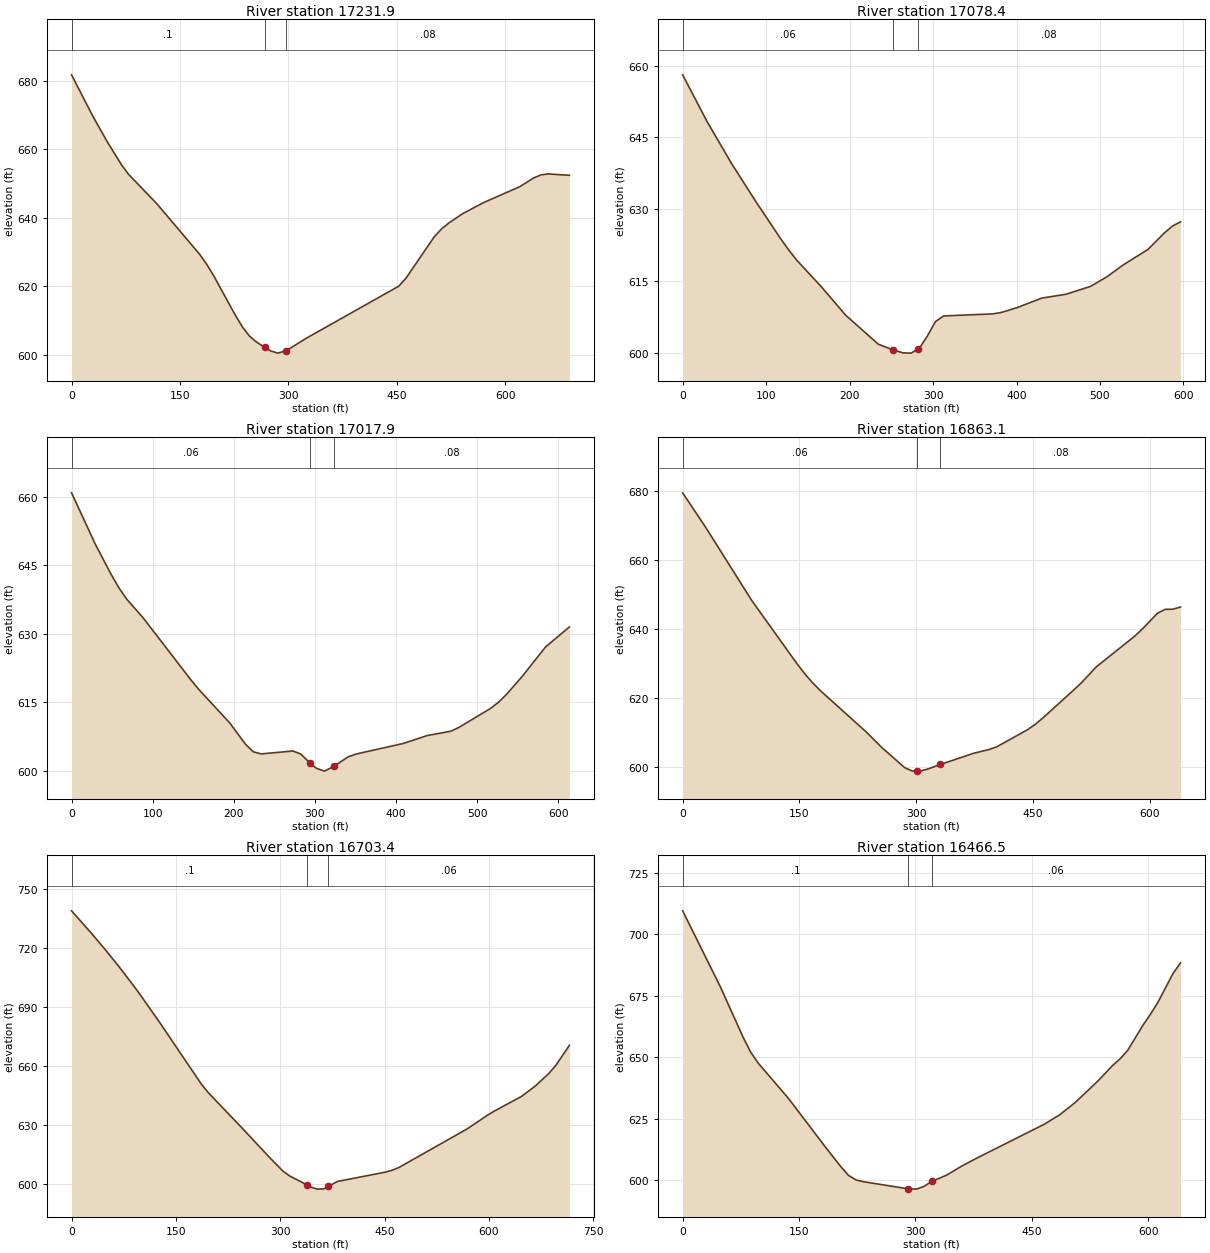
Type RM Length L Ch R = 1 ,17231.9 ,131.8,153.5,161.8
XS GIS Cut Line= 2
     1715222.372        521974.4      1715774.93      522385.886
#Sta/Elev= 30
       0  681.66    29.5  669.57    49.2  662.21    68.9  655.49    78.7  652.68
   118.1  644.04   177.2  629.32     187  626.41   196.8     623   226.4  611.62
   236.2   608.2     246  605.49   255.9  603.71   267.3  602.18   275.6  601.11
   285.4  600.48   297.3   601.2   324.8  604.82   452.7     620   462.6  622.29
   501.9  634.42   511.8  636.66   521.6  638.37   541.3  641.18   570.8  644.46
     620  649.01   639.7   651.6   649.6  652.48   659.4  652.75   688.9  652.36
#Mann= 3 , 0 , 0
       0      .1       0   267.3    .045       0   297.3     .08       0
Bank Sta=267.3,297.3
XS Rating Curve= 0 ,0
Exp/Cntr=0.3,0.1

Type RM Length L Ch R = 1 ,17078.4 ,71.3,60.5,60.4
XS GIS Cut Line= 3
     1715240.879      522059.534     1715491.251      522372.278
     1715648.927      522488.526
#Sta/Elev= 30
       0  658.06    29.3   648.3    58.6  639.56    87.9  631.58   117.2  623.95
     127  621.57   136.8  619.39   166.1  613.89   195.4  607.93   234.5  601.89
   251.8  600.74   263.8   600.1   273.6  600.04   281.8  600.84   283.4     601
   293.1  603.58   302.9  606.62   312.7  607.79   371.3  608.22   381.1  608.48
   400.6  609.52     430   611.5   459.4  612.32   488.8  613.96   508.4  615.96
     528  618.45   557.3  621.63   576.9  625.06   586.7  626.52   596.5  627.41
#Mann= 3 , 0 , 0
       0     .06       0   251.8    .045       0   281.8     .08       0
Bank Sta=251.8,281.8
XS Rating Curve= 0 ,0
Exp/Cntr=0.3,0.1

Type RM Length L Ch R = 1 ,17017.9 ,173.4,154.7,135.4
XS GIS Cut Line= 3
     1715198.325      522084.925     1715454.069      522404.377
     1715618.663      522525.726
#Sta/Elev= 30
       0  660.86    29.2  649.65    48.7  643.03    58.5  640.02    68.2  637.54
    87.7  633.61   146.2  620.12   155.9     618   194.9   610.5   214.4  605.82
   224.1  604.16   233.8   603.7   272.8  604.34   282.6  603.67   293.4  601.78
     302  600.54   311.8  599.93   323.4  600.98     341  603.06   350.8  603.67
   409.2     606   438.4  607.72   467.6  608.67   477.4  609.49   516.3  613.64
   526.1  614.98   535.8  616.66   555.3  620.62   584.5  627.16   613.7  631.49
#Mann= 3 , 0 , 0
       0     .06       0   293.4    .045       0   323.4     .08       0
Bank Sta=293.4,323.4
XS Rating Curve= 0 ,0
Exp/Cntr=0.3,0.1

Type RM Length L Ch R = 1 ,16863.1 ,159.3,159.7,159
XS GIS Cut Line= 2
     1715079.972      522374.384     1715689.407       522567.58
#Sta/Elev= 30
       0  679.58    29.5  669.57    88.5  648.35   147.5  629.68   157.4  626.79
   167.2  624.26     177  622.02   236.1  609.98   255.7  605.53   285.2  599.66
   295.1  598.66     301  598.66   304.9  598.66   314.7  599.27     331   600.6
   373.8  603.86   393.4  604.94   403.3  605.73   442.6  610.67   452.4   612.2
   462.3  614.06   501.6  622.14   511.5  624.22   531.1  628.96   580.3  637.87
   590.1  639.94   609.8  644.59   619.6   645.7   629.5  645.74   639.3  646.38
#Mann= 3 , 0 , 0
       0     .06       0     301    .045       0     331     .08       0
Bank Sta=301,331
XS Rating Curve= 0 ,0
Exp/Cntr=0.3,0.1

Type RM Length L Ch R = 1 ,16703.4 ,230,236.9,243.4
XS GIS Cut Line= 2
     1714990.799       522520.44     1715686.967      522686.338
#Sta/Elev= 30
       0  738.73    29.4  726.99      49  718.82    68.6  710.23    88.2   701.2
      98  696.51   127.4  681.73   186.3  650.98   196.1  646.66   245.1  628.55
   284.3  613.75   303.9  606.69   313.7  604.21     339   599.6   343.1  598.75
   352.9  597.55   362.7  597.66     369  598.96   382.3  601.45     451  606.16
   460.8  607.11   470.6  608.52   568.6  628.08     598  635.07   607.8  637.15
     647  644.62   666.6  649.83   686.2  656.23   696.1  660.31   715.7  670.51
#Mann= 3 , 0 , 0
       0      .1       0     339    .045       0     369     .06       0
Bank Sta=339,369
XS Rating Curve= 0 ,0
Exp/Cntr=0.3,0.1

Type RM Length L Ch R = 1 ,16466.5 ,426.7,409.3,391.5
XS GIS Cut Line= 2
     1715023.646      522699.242     1715600.794      522979.683
#Sta/Elev= 30
       0  709.55    48.6  678.62    77.8   658.2    87.5  652.14    97.2  647.64
   136.1  633.34   184.7  613.14   204.2  605.33   213.9  601.86   223.6  600.03
   233.3  599.31     291  596.42   301.4  596.31   311.1  597.42     321  599.45
   340.3  602.01   359.7  605.68   379.2  608.94   466.7  622.81   486.1   626.6
   505.6  631.46   534.7  640.15   554.2  646.61   563.9  649.35   573.6  652.77
   593.1  662.92   602.8  667.38   612.5  672.27     632  684.03   641.7   688.4
#Mann= 3 , 0 , 0
       0      .1       0     291    .045       0     321     .06       0
Bank Sta=291,321
XS Rating Curve= 0 ,0
Exp/Cntr=0.3,0.1

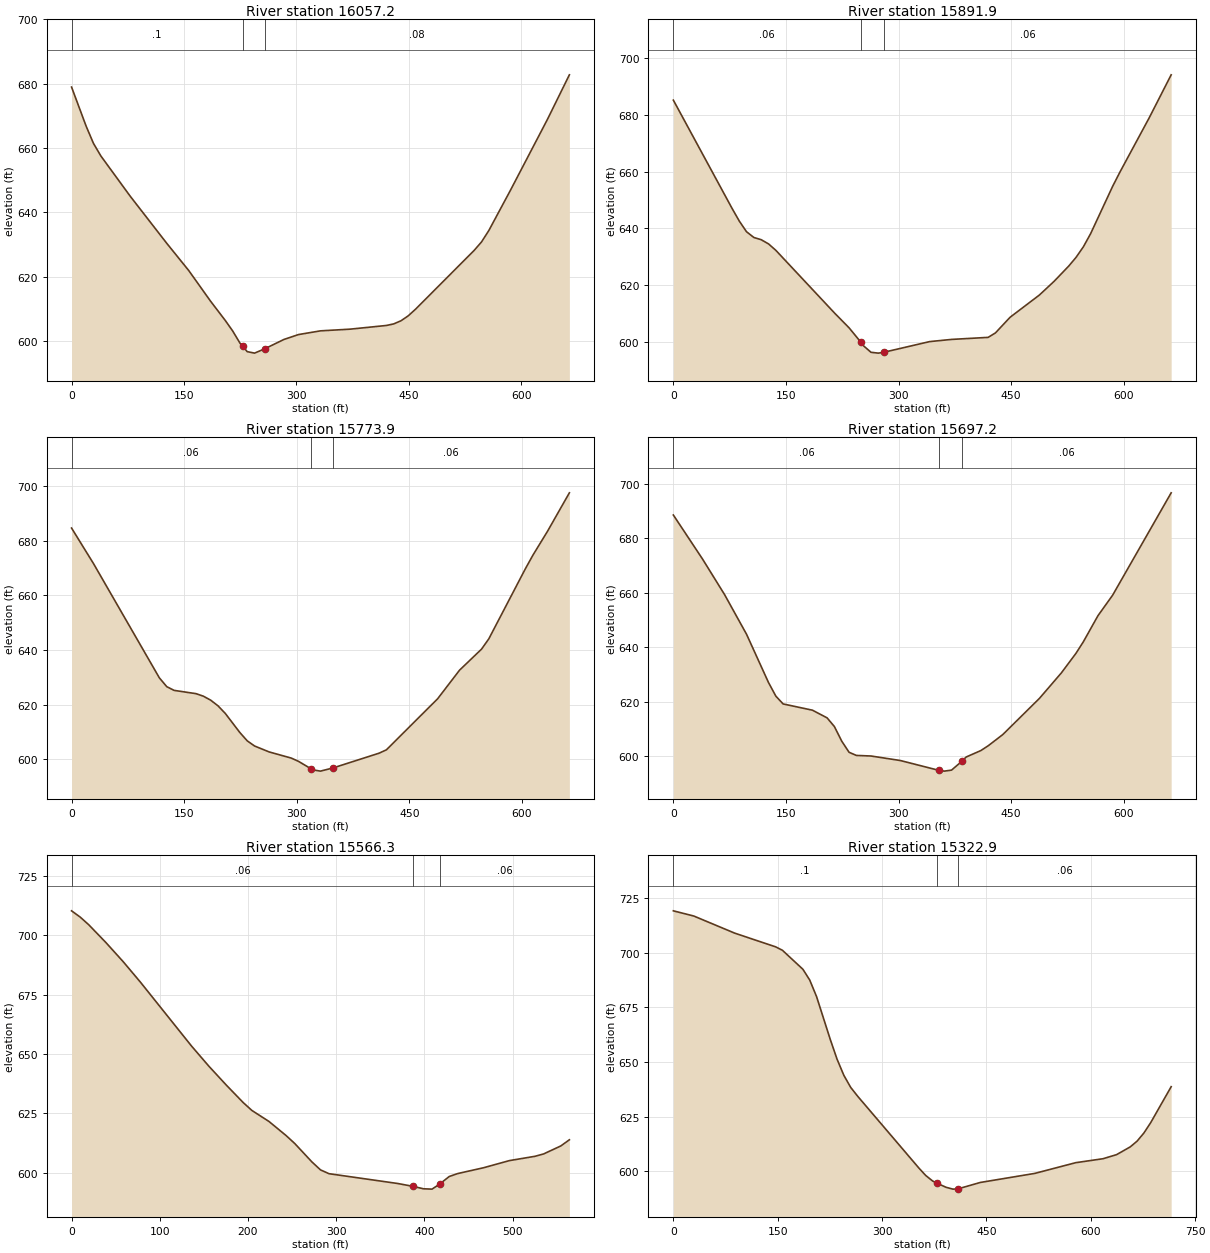
Type RM Length L Ch R = 1 ,16057.2 ,160.6,165.3,170
XS GIS Cut Line= 2
     1714872.224      523134.094     1715533.034      523066.642
#Sta/Elev= 30
       0  678.92    19.5  666.74    29.3  661.39    39.1  657.51    78.2  645.02
     127  630.37   156.3  621.92   185.6  612.34   205.1  606.39   214.9  603.15
   224.7  599.35   228.3  598.37   234.4   596.7   244.2  596.24   258.3  597.65
   283.3  600.48   302.8  602.01   332.1  603.16   371.2  603.68     420  604.83
   429.8  605.32   439.6   606.3   449.3  607.85   459.1  609.92   537.3   628.2
     547   630.8   556.8  634.36   586.1  647.08   634.9  668.86   664.2  682.72
#Mann= 3 , 0 , 0
       0      .1       0   228.3    .045       0   258.3     .08       0
Bank Sta=228.3,258.3
XS Rating Curve= 0 ,0
Exp/Cntr=0.3,0.1

Type RM Length L Ch R = 1 ,15891.9 ,110.8,118,122.6
XS GIS Cut Line= 2
     1714863.569      523265.338     1715526.502      523284.909
#Sta/Elev= 30
       0  685.13      78  647.17    87.8  642.63    97.5  638.85   107.3  636.83
     117  636.06   126.8  634.58   136.6   632.3   214.6  610.31   234.1  605.07
     250  599.96   253.6  598.69   263.3  596.46   273.1  596.17     280  596.45
   341.4  600.22   370.6  600.99   419.4  601.71   429.1  603.28   448.6  608.78
   487.7  616.61   507.2  621.41   526.7  626.77   536.4  629.81   546.2  633.54
   555.9  638.18   585.2   654.8     595  659.86     634  678.94   663.2  694.03
#Mann= 3 , 0 , 0
       0     .06       0     250    .045       0     280     .06       0
Bank Sta=250,280
XS Rating Curve= 0 ,0
Exp/Cntr=0.3,0.1

Type RM Length L Ch R = 1 ,15773.9 ,84.3,76.7,71.6
XS GIS Cut Line= 2
     1714866.381      523355.539     1715529.314       523375.11
#Sta/Elev= 30
       0  684.69    29.3  671.63     117  629.76   126.8  626.55   136.6  625.18
   165.8  623.98   175.6  623.05   185.3   621.6   195.1  619.52   204.8  616.73
   224.3   609.7   234.1  606.67   243.8  604.79   263.3  602.61   292.6  600.37
   302.4  599.16   318.6   596.5   321.9  596.02   331.6  595.58   348.6  596.77
   409.6  602.15   419.4  603.38   487.7  622.11   516.9  632.59   546.2  640.31
   555.9  644.09   604.7  669.83   614.5  674.69     634  683.47   663.2   697.6
#Mann= 3 , 0 , 0
       0     .06       0   318.6    .045       0   348.6     .06       0
Bank Sta=318.6,348.6
XS Rating Curve= 0 ,0
Exp/Cntr=0.3,0.1

Type RM Length L Ch R = 1 ,15697.2 ,127.6,130.9,133.8
XS GIS Cut Line= 2
     1714864.444      523421.144     1715527.377      523440.715
#Sta/Elev= 30
       0  688.56      39  672.35    68.3  659.33    97.5  644.81   126.8  627.08
   136.6  622.08   146.3  619.23   185.3  616.94   204.8  614.13   214.6  610.92
   224.3  605.59   234.1   601.5   243.8  600.34   263.3  600.13   302.4  598.47
   354.3  594.83   360.9  594.58   370.6  594.95   384.3  598.17   390.1  599.76
   409.6  602.12   419.4  603.87   438.9     608   487.7  621.27   516.9  630.62
   536.4  637.81   546.2  642.04   565.7  651.62   585.2  659.13   663.2   696.7
#Mann= 3 , 0 , 0
       0     .06       0   354.3    .045       0   384.3     .06       0
Bank Sta=354.3,384.3
XS Rating Curve= 0 ,0
Exp/Cntr=0.3,0.1

Type RM Length L Ch R = 1 ,15566.3 ,262.5,243.4,224.1
XS GIS Cut Line= 2
     1714822.715      523500.333     1715381.205      523581.787
#Sta/Elev= 30
       0  710.33     9.7  707.72    19.5  704.46    38.9  696.98    58.4  688.96
    77.8   680.4   136.2  653.26   155.7  644.85   175.2  636.99   194.6  629.53
   204.4  626.22   223.8  621.57   243.3  615.61     253  612.29   272.5  604.52
   282.2  601.17   291.9  599.55   369.8  595.42   387.3  594.21     399  593.19
   408.7  593.05   417.3  595.17   428.2  598.37   437.9  599.62   467.1  602.06
   496.3  605.06   525.5  606.89   535.2  607.88   554.7  611.25   564.4  613.84
#Mann= 3 , 0 , 0
       0     .06       0   387.3    .045       0   417.3     .06       0
Bank Sta=387.3,417.3
XS Rating Curve= 0 ,0
Exp/Cntr=0.3,0.1

Type RM Length L Ch R = 1 ,15322.9 ,472.2,473,464.6
XS GIS Cut Line= 2
     1714791.977       523903.77     1715430.573      523580.794
#Sta/Elev= 30
       0  719.16    29.4  716.78    88.2  708.95     147  702.68   156.8  701.11
   186.3  692.39   196.1  687.45   205.9  679.88   225.5  660.38   235.3   651.3
   245.1  643.88   254.9  638.38   264.7  634.41   352.9  601.48   362.7  598.08
   372.5  595.57   378.5  594.58   392.1  592.64   401.9  591.81   408.5  591.87
   441.1  594.85   519.6  599.01   578.4  603.91   617.6  605.72   637.2   607.6
   656.8  611.15   666.6  613.76   676.4  617.49   686.2  622.25   715.6  638.68
#Mann= 3 , 0 , 0
       0      .1       0   378.5    .045       0   408.5     .06       0
Bank Sta=378.5,408.5
XS Rating Curve= 0 ,0
Exp/Cntr=0.3,0.1

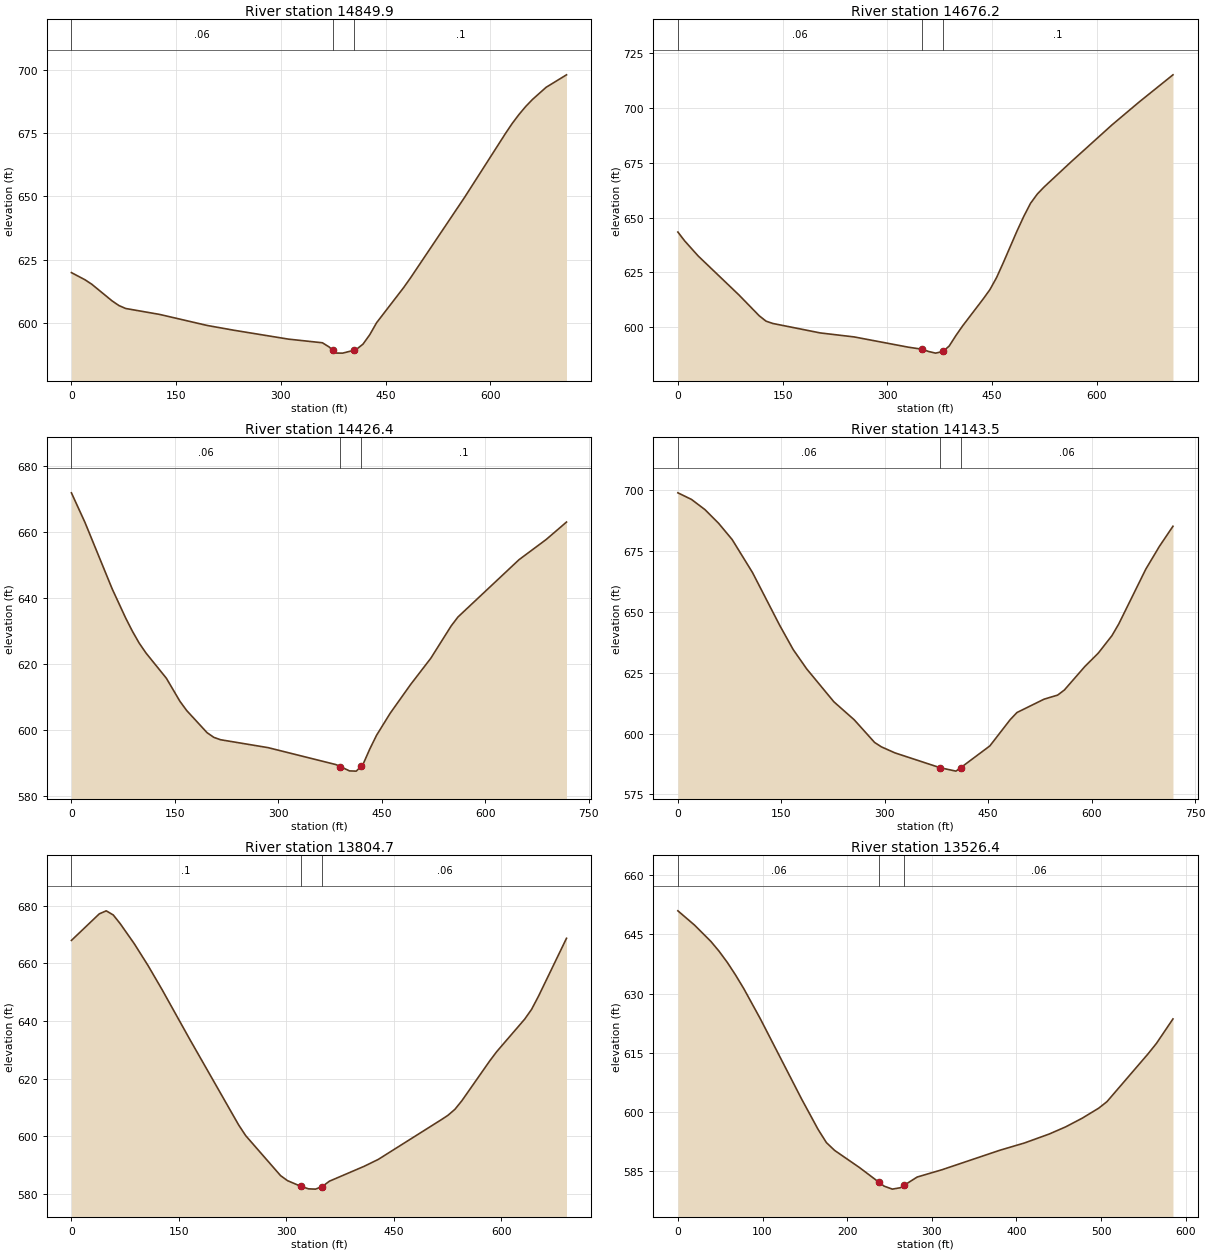
Type RM Length L Ch R = 1 ,14849.9 ,172.7,173.7,175
XS GIS Cut Line= 2
     1715145.535      524195.669     1715611.924       523661.69
#Sta/Elev= 30
       0  619.91    19.4  617.09    29.1  615.33    58.3  608.73      68  606.91
    77.7  605.74   126.3   603.4   194.2  599.05   233.1  597.13   310.8  593.64
   359.4   592.2   369.1  590.54   374.7  589.15   378.8  588.14   388.5  588.11
   404.7  589.25   407.9  589.55   417.6  591.67   427.3   595.4     437   600.1
   475.9  614.04   485.6  617.82   563.3  649.74   621.6  674.86   631.3  678.84
     641  682.38   650.7  685.56   660.4  688.33   679.8   693.1     709  698.03
#Mann= 3 , 0 , 0
       0     .06       0   374.7    .045       0   404.7      .1       0
Bank Sta=374.7,404.7
XS Rating Curve= 0 ,0
Exp/Cntr=0.3,0.1

Type RM Length L Ch R = 1 ,14676.2 ,241.2,249.8,257.7
XS GIS Cut Line= 2
     1715278.491      524301.129      1715744.88      523767.149
#Sta/Elev= 30
       0  643.43     9.7   639.4    29.1   632.5    87.4  614.74   116.5  605.22
   126.3  602.76     136  601.71     204  597.39   252.5  595.57   330.2  590.88
   349.6  589.97   359.4   588.9   369.1  588.18   379.6  588.95   388.5   591.4
   398.2  596.23   407.9  600.66     437   612.8   446.8  617.13   456.5  622.72
   466.2  629.58   485.6  643.86   495.3  650.54     505  656.53   514.7  660.76
   524.4  663.97   563.3  675.52   621.6   692.3   660.4  702.72     709  715.17
#Mann= 3 , 0 , 0
       0     .06       0   349.6    .045       0   379.6      .1       0
Bank Sta=349.6,379.6
XS Rating Curve= 0 ,0
Exp/Cntr=0.3,0.1

Type RM Length L Ch R = 1 ,14426.4 ,275.2,282.9,290.6
XS GIS Cut Line= 2
     1715373.956      524417.408        1715960.      524002.823
#Sta/Elev= 30
       0  671.76    19.7  662.79      59  642.77    78.7  633.89    88.5  629.89
    98.3  626.31   108.2  623.31   137.7  615.69   157.3  608.74   167.2  605.92
   196.7  599.24   206.5  597.82   216.3   597.1   285.2  594.71   383.5  589.59
   390.1  588.98   403.2  587.68     413  587.61   420.1  589.07   422.8  589.63
   432.7  594.32   442.5  598.46   462.2   605.1   491.7  613.76   521.2  621.76
   550.7  631.52   560.5  634.21     649  651.53   688.4  657.64   717.9  662.92
#Mann= 3 , 0 , 0
       0     .06       0   390.1    .045       0   420.1      .1       0
Bank Sta=390.1,420.1
XS Rating Curve= 0 ,0
Exp/Cntr=0.3,0.1

Type RM Length L Ch R = 1 ,14143.5 ,340.8,338.8,333.6
XS GIS Cut Line= 2
     1715426.516      524547.078     1716101.913      524303.833
#Sta/Elev= 30
       0  699.02    19.7  696.31    39.3   692.1      59   686.5    78.7   679.8
   108.2  666.22   147.5  644.58   167.2  634.54   186.8  626.58   226.2  613.05
   255.7  605.65   285.2  596.34     295  594.53   314.7  592.04   380.5  585.91
   403.2  584.53   410.5  586.02   452.4  594.91   481.8  605.68   491.7  608.64
     531  614.13   550.7  615.81   560.5  617.92     590  627.53   609.7  633.11
   629.4  640.26   639.2  645.02   678.5  667.61   698.2  676.98   717.9  685.27
#Mann= 3 , 0 , 0
       0     .06       0   380.5    .045       0   410.5     .06       0
Bank Sta=380.5,410.5
XS Rating Curve= 0 ,0
Exp/Cntr=0.3,0.1

Type RM Length L Ch R = 1 ,13804.7 ,279.3,278.3,274.7
XS GIS Cut Line= 2
     1715568.406      524814.635      1716215.89      524573.648
#Sta/Elev= 30
       0  667.94    38.9  677.16    48.6  678.21    58.4  676.77    68.1  673.75
    87.6  666.84     107  659.19   126.5  650.87   165.4  633.51   233.5  603.85
   243.3  600.16   291.9   586.3   301.6  584.56   320.1   582.6   330.8  581.72
   340.6  581.62   350.1  582.52     360  584.37   408.7  589.56   428.2  591.93
   515.7  605.64   525.4  607.22   535.2  609.32   544.9   612.3   583.8  626.13
   593.6  629.36   632.5   640.6   642.2  644.02     652  648.66   690.9  668.67
#Mann= 3 , 0 , 0
       0      .1       0   320.1    .045       0   350.1     .06       0
Bank Sta=320.1,350.1
XS Rating Curve= 0 ,0
Exp/Cntr=0.3,0.1

Type RM Length L Ch R = 1 ,13526.4 ,287.5,302.2,316.9
XS GIS Cut Line= 2
     1715747.876      525027.259     1716278.105      524780.372
#Sta/Elev= 30
       0  650.94    19.5  647.36      39  643.19    48.7   640.7    58.5  637.85
    68.2  634.67      78  631.19    97.5  623.57   146.2  603.28   165.7  595.58
   175.5  592.25   185.2  590.28   214.5  585.95   237.5  582.23   243.7  581.23
   253.4  580.48   263.2  580.85   267.5  581.48   282.7  583.54   311.9  585.38
   380.2  590.31   409.4  592.16   438.7  594.43   458.2  596.25   477.7  598.44
   497.2  600.98   506.9  602.62   555.6  614.76   565.4  617.38   584.9  623.57
#Mann= 3 , 0 , 0
       0     .06       0   237.5    .045       0   267.5     .06       0
Bank Sta=237.5,267.5
XS Rating Curve= 0 ,0
Exp/Cntr=0.3,0.1

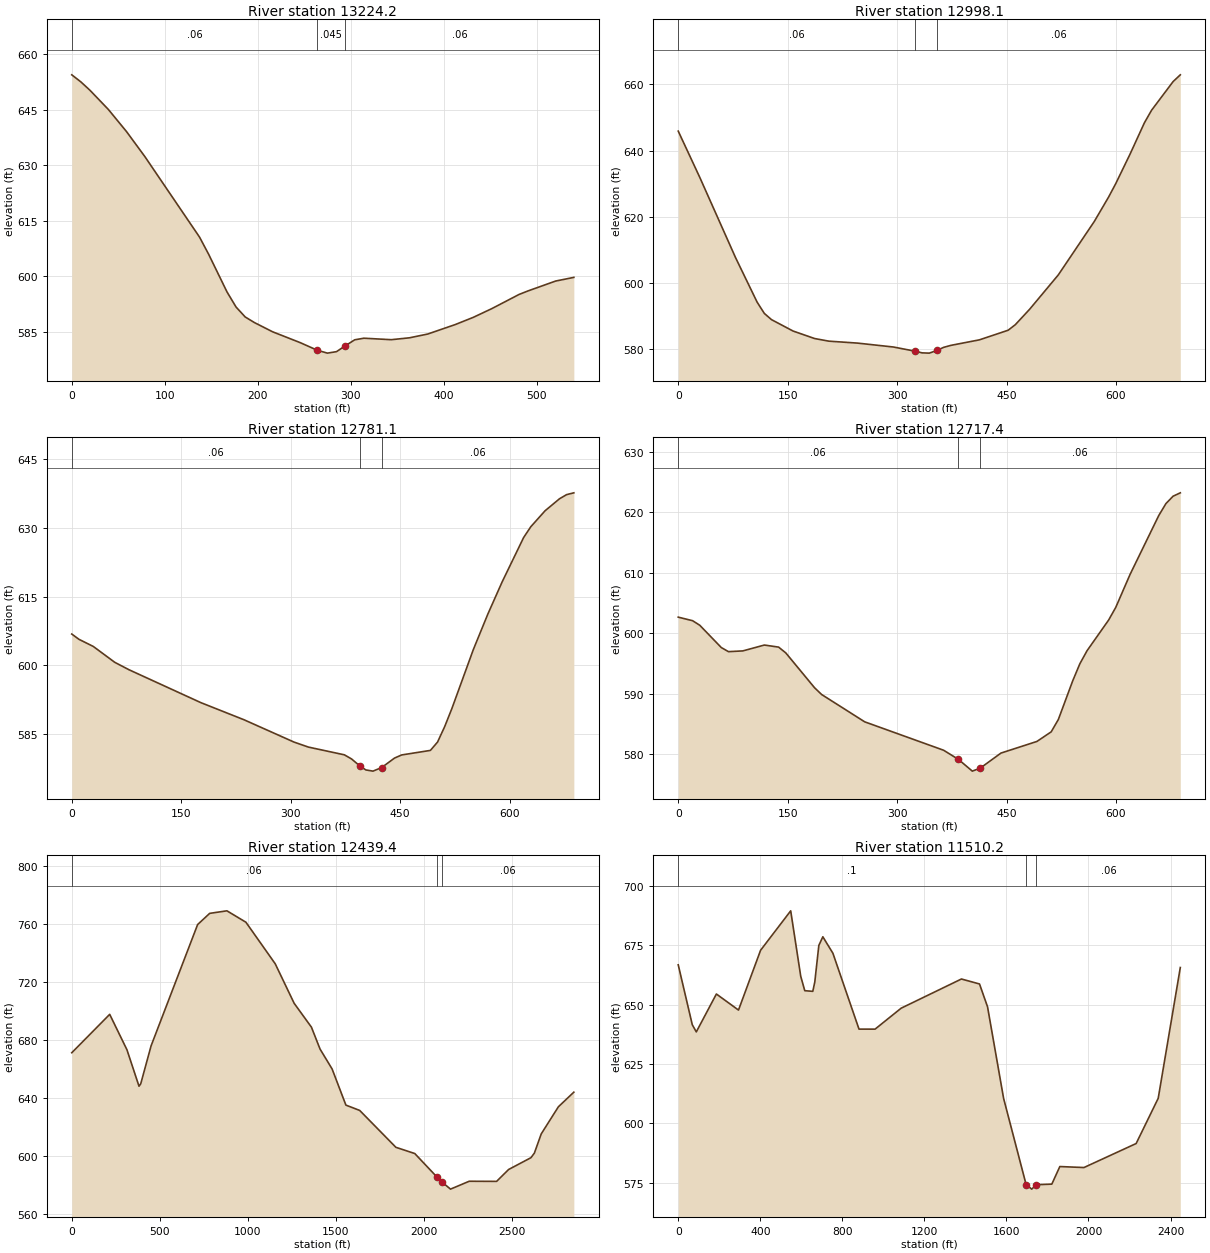
Type RM Length L Ch R = 1 ,13224.2 ,220.8,226.1,230.7
XS GIS Cut Line= 2
     1715803.064      525184.542     1716342.558      525205.748
#Sta/Elev= 30
       0  654.44     9.8  652.53    19.6  650.26    39.3   645.1    58.9   639.1
    78.5  632.39   137.4   610.6   147.2  605.96   166.9  595.81   176.7   591.7
   186.5  589.03   196.3  587.53     216  585.02   245.4  582.12     264  580.04
   274.9  579.26   284.7  579.66     294  581.22   304.3  582.86   314.1  583.29
   343.6  582.89   363.2   583.4   382.8  584.42   412.3  586.97   431.9  588.94
   451.6  591.27     481  595.11   490.8  596.08   520.3  598.73   539.9  599.72
#Mann= 3 , 0 , 0
       0     .06       0     264    .045       0     294     .06       0
Bank Sta=264,294
XS Rating Curve= 0 ,0
Exp/Cntr=0.3,0.1

Type RM Length L Ch R = 1 ,12998.1 ,224.9,217,209.7
XS GIS Cut Line= 2
     1715758.825      525353.178     1716433.739      525487.573
#Sta/Elev= 30
       0  645.87    29.5   631.9    78.6  607.61   108.1  594.18     118  590.76
   127.8  588.88   157.3  585.44   186.8  583.17   206.4  582.37   245.8  581.78
   294.9   580.6     325  579.32   334.2  578.83   344.1  578.75     355  579.59
   363.7  580.49   373.6  581.09   412.9  582.77   452.2  585.67     462  587.34
   481.7  592.02     521  602.41   570.2  618.52   589.9  625.93   599.7     630
   619.4  638.96     639  648.39   648.8  652.18   678.3  660.84   688.2  662.89
#Mann= 3 , 0 , 0
       0     .06       0     325    .045       0     355     .06       0
Bank Sta=325,355
XS Rating Curve= 0 ,0
Exp/Cntr=0.3,0.1

Type RM Length L Ch R = 1 ,12781.1 ,63.3,63.7,64
XS GIS Cut Line= 2
     1715666.913      525649.671     1716354.489      525621.189
#Sta/Elev= 30
       0  606.84     9.8   605.7    29.5  604.14      59  600.68    78.6  599.06
     177  591.91   235.9   588.2   304.8  583.32   324.4  582.24   373.6  580.56
   383.4  579.67   394.8  578.15   403.1  577.27   412.9  577.01   424.8  577.79
   442.4  579.85   452.2  580.53   491.6  581.52   501.4  583.34   511.2  586.71
     521  590.62   550.5  603.49   570.2  611.14   589.9  618.18   619.4  627.85
   629.2  630.19   648.8  633.67   668.5  636.27   678.3  637.18   688.2  637.57
#Mann= 3 , 0 , 0
       0     .06       0   394.8    .045       0   424.8     .06       0
Bank Sta=394.8,424.8
XS Rating Curve= 0 ,0
Exp/Cntr=0.3,0.1

Type RM Length L Ch R = 1 ,12717.4 ,257.8,278,300.6
XS GIS Cut Line= 2
     1715666.202      525711.112     1716353.778      525682.629
#Sta/Elev= 30
       0  602.67    19.7  602.08    29.5  601.33      59  597.64    68.8  596.96
    88.5  597.08     118  598.05   137.6  597.71   147.5  596.74   186.8  590.99
   196.6  589.86   255.6  585.34   363.7  580.64   383.9  579.14   403.1  577.18
   413.9  577.67   442.4  580.17   491.6  582.09   511.2  583.68     521  585.72
   540.7  592.12   550.5  594.95   560.4  597.12   589.9  602.18   599.7  604.28
   619.4  609.76   658.7   619.5   668.5  621.47   678.3  622.69   688.2  623.25
#Mann= 3 , 0 , 0
       0     .06       0   383.9    .045       0   413.9     .06       0
Bank Sta=383.9,413.9
XS Rating Curve= 0 ,0
Exp/Cntr=0.3,0.1

Type RM Length L Ch R = 1 ,12439.4 ,981.8,929.2,890.9
XS GIS Cut Line= 4
     1714009.298      526635.722      1715721.92      525766.358
     1716064.884      525922.667     1716594.546      525753.381
#Sta/Elev= 30
       0  671.11   215.6  697.59   313.6  673.17   382.2  648.03     392  649.71
   450.8  675.86   715.3  759.51   783.9  767.23   881.9  768.98   989.7  761.13
  1156.3  732.47  1264.1  705.19  1362.1  688.76  1411.1  673.66  1479.7  659.91
  1558.1     635  1636.5  631.33  1842.2   605.9  1949.6   601.6  2073.7  585.65
  2103.7     582  2152.6  577.06  2258.9  582.49  2414.6   582.4  2482.9   590.6
  2609.7  598.73  2629.2  601.88  2668.2  615.13  2765.8  633.85  2853.6  643.92
#Mann= 3 , 0 , 0
       0     .06       0  2073.7    .045       0  2103.7     .06       0
Bank Sta=2073.7,2103.7
XS Rating Curve= 0 ,0
Exp/Cntr=0.3,0.1

Type RM Length L Ch R = 1 ,11510.2 ,305.2,313.8,324.1
XS GIS Cut Line= 3
     1715537.172      528044.018     1716095.254      526279.534
     1716595.952      525954.261
#Sta/Elev= 30
       0  666.75    68.5  641.55    88.1  638.53     186  654.47   293.8  647.71
   401.5  672.87   548.3  689.46   597.3  661.89   616.9  655.86     656  655.59
   665.8  659.55   685.4  674.89     705  678.54     754  671.62   881.3   639.7
   959.6  639.69  1086.9  648.51  1380.6  660.78  1468.8  658.69  1507.9  649.09
  1586.3  610.54  1695.9574.3192  1723.4  572.39  1745.9574.2437  1821.3  574.49
  1860.4  581.89  1977.9  581.47  2232.4  591.57    2340   610.6  2447.7  665.62
#Mann= 3 , 0 , 0
       0      .1       0  1695.9    .045       0  1745.9     .06       0
Bank Sta=1695.9,1745.9
XS Rating Curve= 0 ,0
Exp/Cntr=0.3,0.1