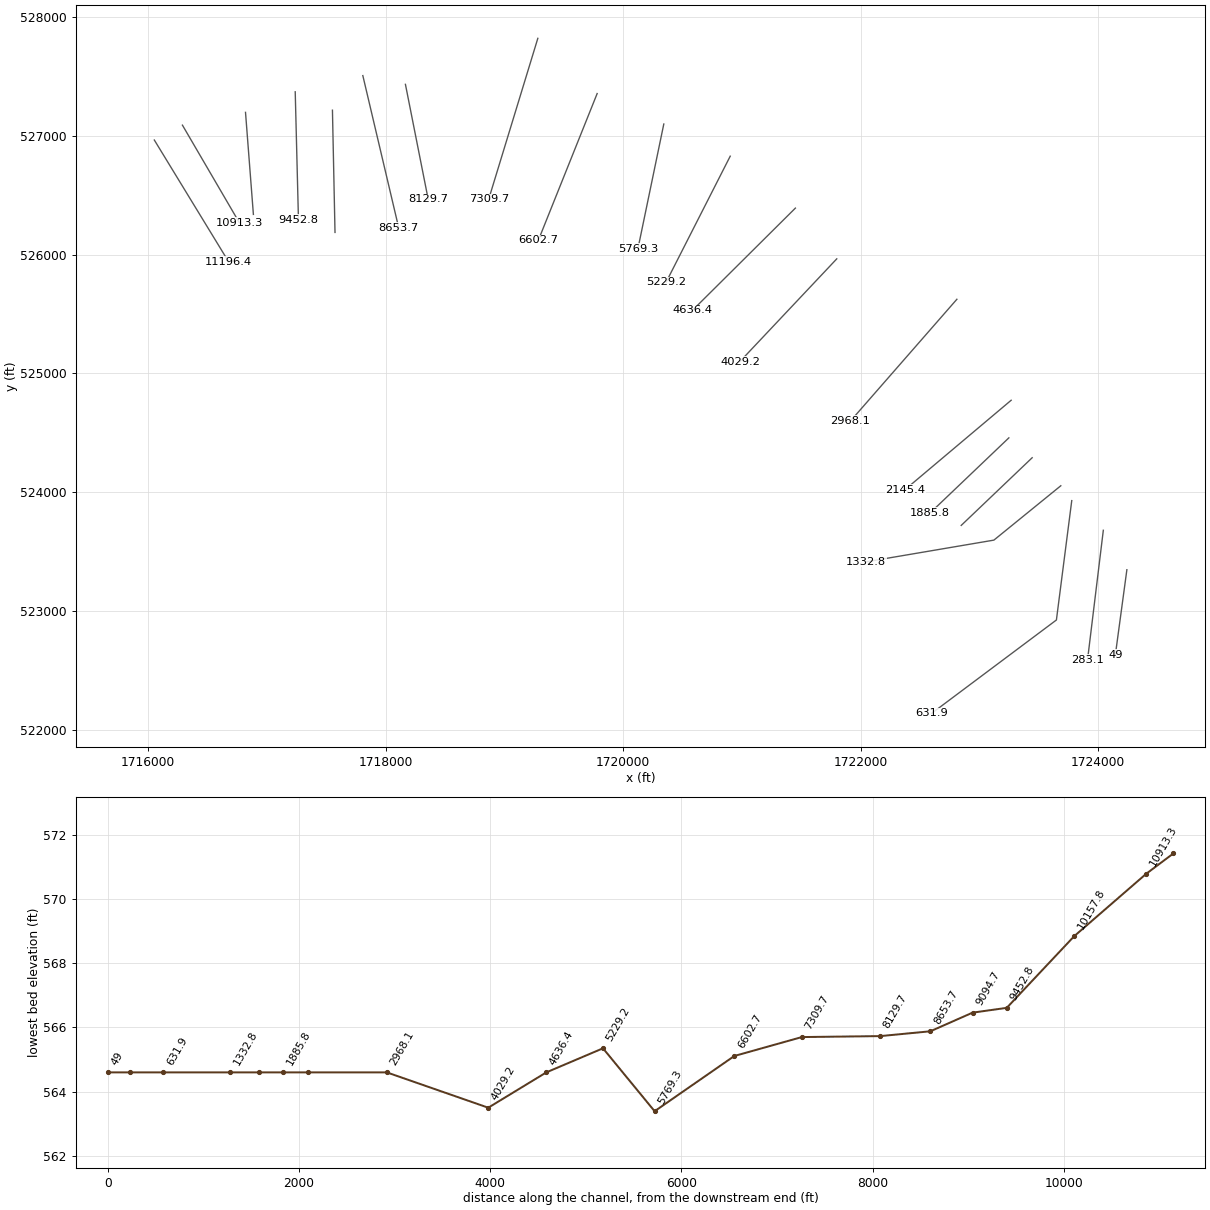
HEC-RAS study ScaryCr.prj: ScaryCr

--- ScaryCr.g01 (geometry) --- (continued)

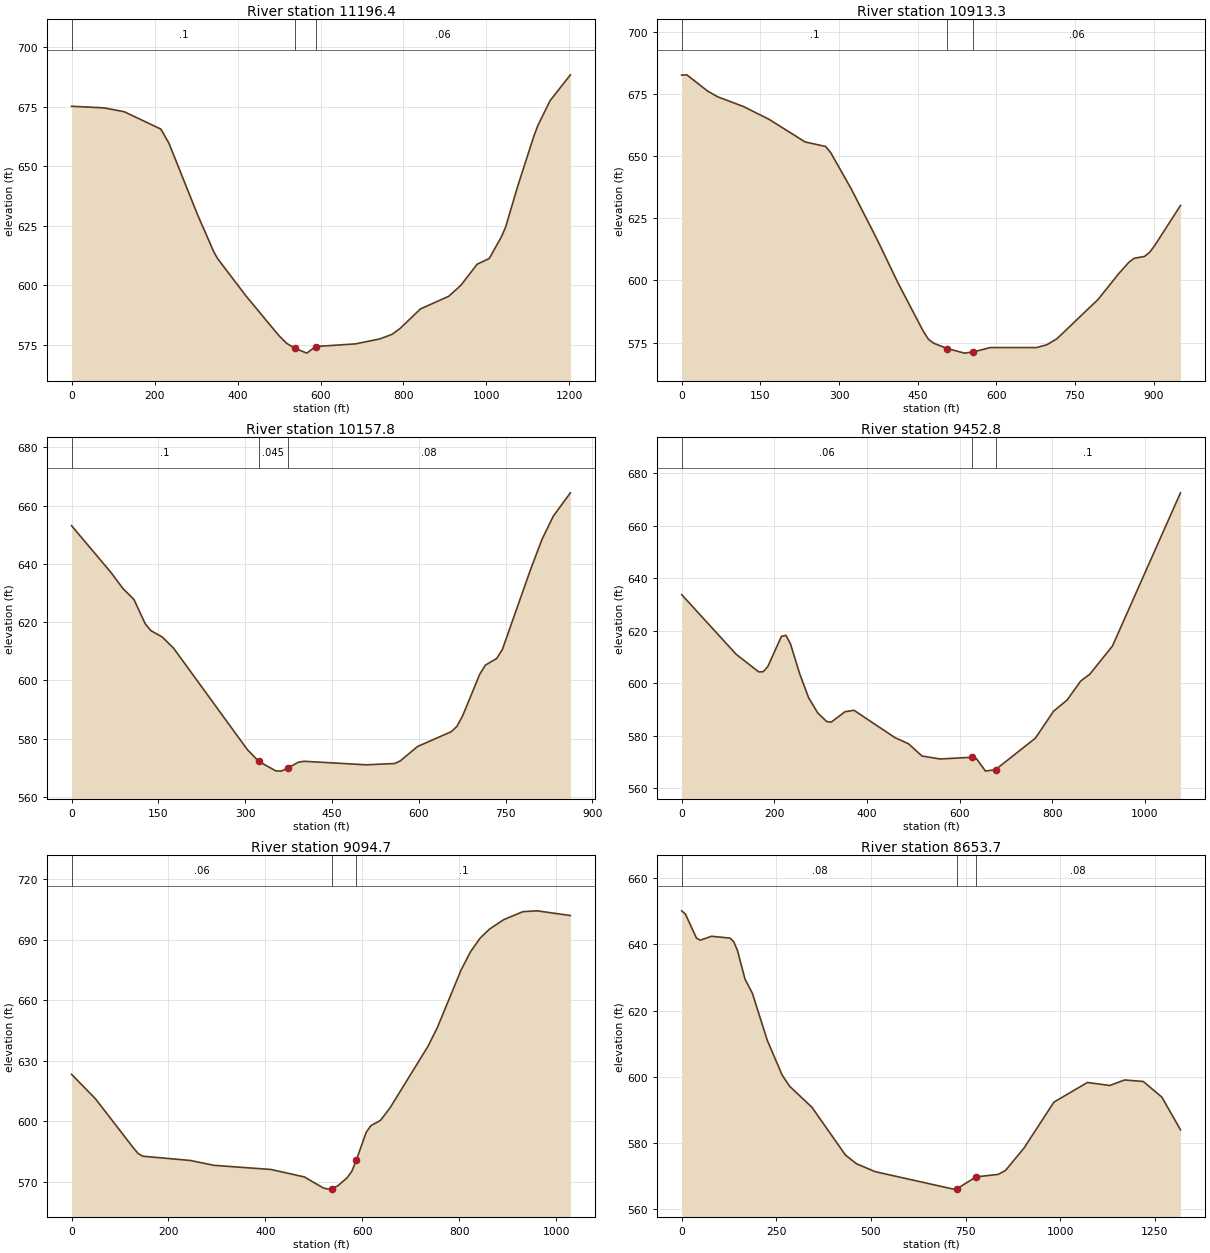
Type RM Length L Ch R = 1 ,11196.4 ,275.2,283.1,286.4
XS GIS Cut Line= 2
     1716051.268      526964.607     1716677.722      525938.308
#Sta/Elev= 30
       0  675.27    78.2   674.6   127.1  672.96   215.1  665.68   234.6  659.76
     303  629.92   342.1  614.28   351.9   611.2   420.4  595.49   498.6  579.02
   518.1  575.59   538.4573.4276     567  571.42   588.4574.1954   684.3  575.31
   742.9  577.39   772.3   579.3   791.8  581.78   840.7  589.99   909.1  595.34
   938.4  599.94   977.6  608.83  1006.9  611.24  1036.2  620.38    1046   624.3
  1075.3  641.58  1114.4  662.74  1124.2  667.25  1153.5  677.65  1202.4   688.5
#Mann= 3 , 0 , 0
       0      .1       0   538.4    .045       0   588.4     .06       0
Bank Sta=538.4,588.4
XS Rating Curve= 0 ,0
Exp/Cntr=0.3,0.1

Type RM Length L Ch R = 1 ,10913.3 ,750.6,755.6,532.6
XS GIS Cut Line= 2
     1716287.964      527089.969     1716767.407      526268.327
#Sta/Elev= 30
       0  682.59     9.8   682.7      49  676.24    68.6  673.86   117.7  669.96
   166.7   664.8   235.4  655.71   274.6  653.89   284.4  651.34   323.6  636.74
   372.7   616.5   411.9   599.3   460.9  579.54   470.7  576.35   480.6  574.78
   506.2572.6502   539.4  570.79   556.2571.2643   588.4  573.03   676.7  573.02
   696.3  574.15   715.9  576.61   794.4  592.44   833.6  602.77   853.2  607.38
     863  608.92   882.6  609.67   892.4   611.3   902.3   614.1   951.3  630.16
#Mann= 3 , 0 , 0
       0      .1       0   506.2    .045       0   556.2     .06       0
Bank Sta=506.2,556.2
XS Rating Curve= 0 ,0
Exp/Cntr=0.3,0.1

Type RM Length L Ch R = 1 ,10157.8 ,700.1,705,692.6
XS GIS Cut Line= 2
     1716819.149      527197.791     1716885.492      526338.281
#Sta/Elev= 30
       0  653.09    68.6  636.92    88.2  631.66   107.8  627.77   127.4  619.37
   137.2  617.06   156.7  614.88   176.3  611.04   303.7  576.25   323.7572.1484
   352.7  568.95   362.5  568.84   373.7 569.902   391.8  571.89   401.6  572.22
   509.4  571.01   558.4  571.46   568.2  572.37   597.6  577.26   656.4   582.4
   666.1  584.22   675.9  587.84   705.3  602.06   715.1  605.22   734.7  607.52
   744.5  610.57   793.5   638.2   813.1  648.44   832.7  656.43   862.1  664.39
#Mann= 3 , 0 , 0
       0      .1       0   323.7    .045       0   373.7     .08       0
Bank Sta=323.7,373.7
XS Rating Curve= 0 ,0
Exp/Cntr=0.3,0.1

Type RM Length L Ch R = 1 ,9452.8  ,355.7,358,363
XS GIS Cut Line= 2
     1717237.802      527370.867     1717265.023      526294.215
#Sta/Elev= 30
       0  633.84   117.5  611.14   166.4  604.41   176.2  604.49     186  606.46
   215.4  617.96   225.2  618.32     235  615.03   254.6   603.8   274.1  594.57
   293.7  588.81   313.3  585.46   323.1   585.3   352.5  589.24     372  589.79
   460.2   579.4   489.5  577.06   518.9  572.36   558.1  571.24   627.9 571.899
   636.4  571.37     656  566.61   677.9567.2062   763.7  579.16   802.8  589.39
   832.2   593.7   861.6  600.93   881.2  603.53   930.1  614.25    1077  672.62
#Mann= 3 , 0 , 0
       0     .06       0   627.9    .045       0   677.9      .1       0
Bank Sta=627.9,677.9
XS Rating Curve= 0 ,0
Exp/Cntr=0.3,0.1

Type RM Length L Ch R = 1 ,9094.7  ,482.3,441,447.3
XS GIS Cut Line= 2
     1717551.211      527216.042     1717572.806      526186.646
#Sta/Elev= 30
       0  623.36      49  611.34   127.5  586.92   137.3  584.12   147.1  582.78
   245.2  580.67   294.2  578.25   411.8   576.2   480.5   572.5   519.7  567.03
   529.5  566.46   537.5566.6559   549.1  568.04   568.7  572.08   578.6  575.39
   587.5580.7028     608  594.58   617.8  597.96   637.4  600.51     657  606.65
   735.4  637.18   755.1  646.65   804.1  675.19   823.7  684.27   843.3  690.93
   862.9  695.45   892.3  700.13   931.6  704.05     961  704.46  1029.6  702.12
#Mann= 3 , 0 , 0
       0     .06       0   537.5    .045       0   587.5      .1       0
Bank Sta=537.5,587.5
XS Rating Curve= 0 ,0
Exp/Cntr=0.3,0.1

Type RM Length L Ch R = 1 ,8653.7  ,473.9,524,516.3
XS GIS Cut Line= 2
     1717807.078      527507.328     1718109.534      526224.553
#Sta/Elev= 30
       0   650.2     9.8  649.23    39.3   641.9    49.2  641.31    78.7  642.49
   127.9  641.94   137.7   640.8   147.5  638.16   167.2  629.53   186.9  625.18
   226.2  610.96   265.6  600.41   285.2  597.05   344.2  590.68   432.8  576.19
   462.3  573.54   511.4  571.17     718  565.88   727.7566.0087   777.7 569.595
     836  570.33   855.7  571.54   904.9  578.38   983.6  592.24  1072.1   598.2
  1131.1  597.28  1170.4  598.95  1219.6   598.5  1268.8  593.76    1318  583.86
#Mann= 3 , 0 , 0
       0     .08       0   727.7    .045       0   777.7     .08       0
Bank Sta=727.7,777.7
XS Rating Curve= 0 ,0
Exp/Cntr=0.3,0.1

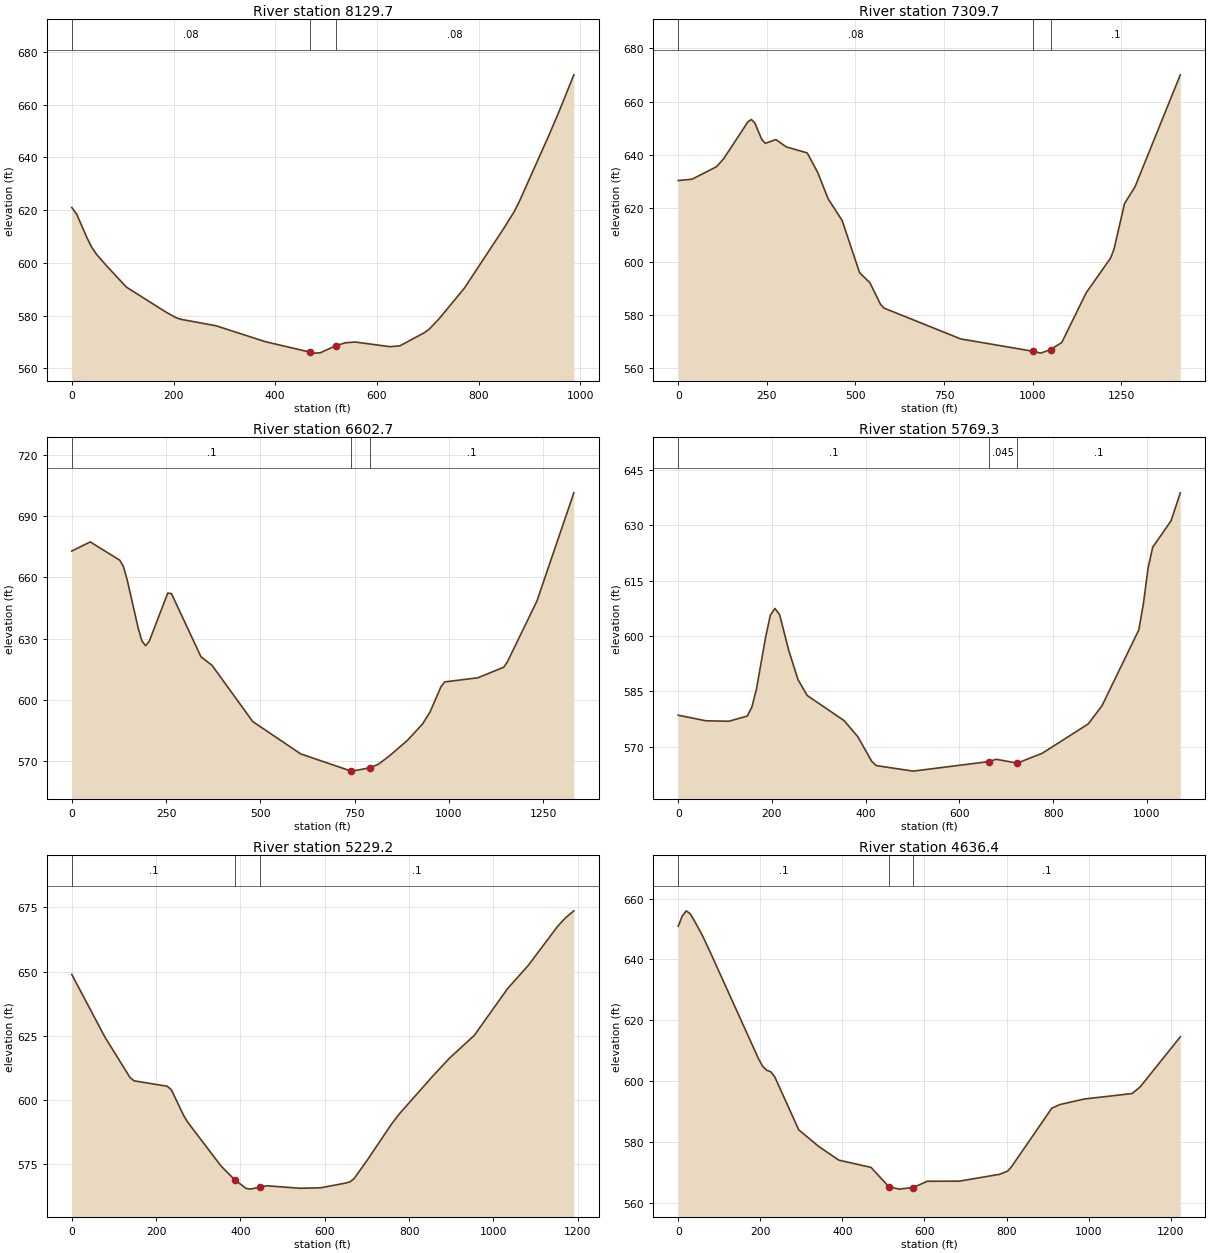
Type RM Length L Ch R = 1 ,8129.7  ,836.3,820,801.4
XS GIS Cut Line= 2
     1718165.814       527433.59      1718357.59      526465.427
#Sta/Elev= 30
       0  620.98     9.8  618.42    29.3  609.76    39.1  605.95    48.9  603.16
    68.4  598.86   107.5  590.77   185.7  581.23   205.2  579.15     215  578.54
   283.4  576.12   381.1  570.04   468.5566.0988   478.8  565.73   488.6  565.88
   518.5568.5047   537.5  569.64     557  569.95   625.4  568.17     645  568.49
   693.8  573.55   703.6     575   723.1  578.99     772  590.43   850.2  613.34
   869.7   619.4   879.5  623.11   938.1  648.43   957.7   657.3     987  671.32
#Mann= 3 , 0 , 0
       0     .08       0   468.5    .045       0   518.5     .08       0
Bank Sta=468.5,518.5
XS Rating Curve= 0 ,0
Exp/Cntr=0.3,0.1

Type RM Length L Ch R = 1 ,7309.7  ,712.1,706.9,701
XS GIS Cut Line= 2
     1719280.764      527821.089        1718867.       526466.23
#Sta/Elev= 30
       0  630.43    39.4  630.94   108.2  635.63   127.9  638.56   196.8  652.47
   206.6  653.32   216.4  651.94   236.1   645.7   245.9  644.38   275.5   645.8
     305  643.04     364  640.78   393.5  633.46     423  623.56   462.4  615.46
   511.6  595.91   541.1  592.03   570.6  584.03   580.4   582.6   796.9  571.03
  1000.4566.4081  1023.1   565.7  1050.4567.0328  1082.2  569.69    1151  588.33
  1219.9  601.36  1229.7  604.77  1259.2   621.8  1288.7  628.04  1416.6  670.07
#Mann= 3 , 0 , 0
       0     .08       0  1000.4    .045       0  1050.4      .1       0
Bank Sta=1000.4,1050.4
XS Rating Curve= 0 ,0
Exp/Cntr=0.3,0.1

Type RM Length L Ch R = 1 ,6602.7  ,828.8,833.4,836.2
XS GIS Cut Line= 2
     1719780.397      527356.041     1719284.992      526119.968
#Sta/Elev= 30
       0  672.86      49  677.33   127.3  668.38   137.1  665.23   146.9  658.82
   176.2  635.13     186  628.84   195.8  626.52   205.6  628.73   254.6  652.27
   264.4  652.02   342.7  621.09   372.1  616.89   479.8  589.41   607.1  573.55
   739.9565.2021   744.2  565.11   789.9566.7245   812.7  568.43   842.1  572.51
     891  580.31   930.2  588.18   949.8  593.91   979.2  606.43     989  608.78
  1077.1  610.82  1145.6  615.98  1155.4  618.63  1233.7  648.38  1331.6  701.36
#Mann= 3 , 0 , 0
       0      .1       0   739.9    .045       0   789.9      .1       0
Bank Sta=739.9,789.9
XS Rating Curve= 0 ,0
Exp/Cntr=0.3,0.1

Type RM Length L Ch R = 1 ,5769.3  ,546.2,540.2,535.2
XS GIS Cut Line= 2
     1720341.612      527099.494     1720124.006      526050.767
#Sta/Elev= 30
       0  578.53      59  577.02   108.1   576.9   147.4  578.31   157.2  580.78
     167  585.69   186.7  599.85   196.5   605.6   206.4  607.43   216.2  605.79
   235.8  596.05   255.5  588.18   275.1  583.87   353.8  577.08   383.2  572.69
   412.7  566.06   422.5  564.89   501.1  563.39   663.4565.9853     678   566.6
   723.4565.5654   776.3  568.21   874.5  576.15     904  581.09   982.6  601.64
   992.4  608.76  1002.3  618.34  1012.1  623.98  1051.4  631.18  1071.1  638.74
#Mann= 3 , 0 , 0
       0      .1       0   663.4    .045       0   723.4      .1       0
Bank Sta=663.4,723.4
XS Rating Curve= 0 ,0
Exp/Cntr=0.3,0.1

Type RM Length L Ch R = 1 ,5229.2  ,600.9,592.7,584.5
XS GIS Cut Line= 2
     1720900.959      526828.774     1720361.014      525767.504
#Sta/Elev= 30
       0  648.91    78.7   624.5   137.8  608.88   147.6   607.5   226.3   605.4
   236.2  604.02   265.7  593.89   275.5  591.28   354.3  574.29   386.5568.9801
   413.3  565.66   423.2  565.35   446.5 566.132   462.5  566.66   541.2  565.68
   590.4  565.87   649.5  567.71   659.3  568.16   669.2  569.38   698.7  576.14
   757.7  590.52   777.4  594.75   856.1  609.32   895.5  616.28   954.6  625.18
  1033.3  643.34  1082.5  652.39  1151.4  667.44    1171  670.95  1190.7  673.66
#Mann= 3 , 0 , 0
       0      .1       0   386.5    .045       0   446.5      .1       0
Bank Sta=386.5,446.5
XS Rating Curve= 0 ,0
Exp/Cntr=0.3,0.1

Type RM Length L Ch R = 1 ,4636.4  ,607.6,607.3,606.8
XS GIS Cut Line= 2
      1721449.67      526391.412      1720581.78      525529.316
#Sta/Elev= 30
       0  650.91     9.8  654.27    19.6  655.98    29.4  654.97    39.2  652.75
    58.7  647.94    78.3   642.3   195.7  607.38   205.5  604.96   215.3  603.62
   225.1  603.17   234.9  601.55   293.6  584.07   342.5  578.59   391.4  574.11
   469.7  571.74   512.8565.4418   538.2   564.6   572.8565.1312   606.8  567.18
     685  567.22   782.9  569.47   802.5  570.51   812.3     572   910.1  591.16
   929.7  592.36   988.4  594.17  1105.9  595.99  1125.4  598.15  1223.3  614.61
#Mann= 3 , 0 , 0
       0      .1       0   512.8    .045       0   572.8      .1       0
Bank Sta=512.8,572.8
XS Rating Curve= 0 ,0
Exp/Cntr=0.3,0.1

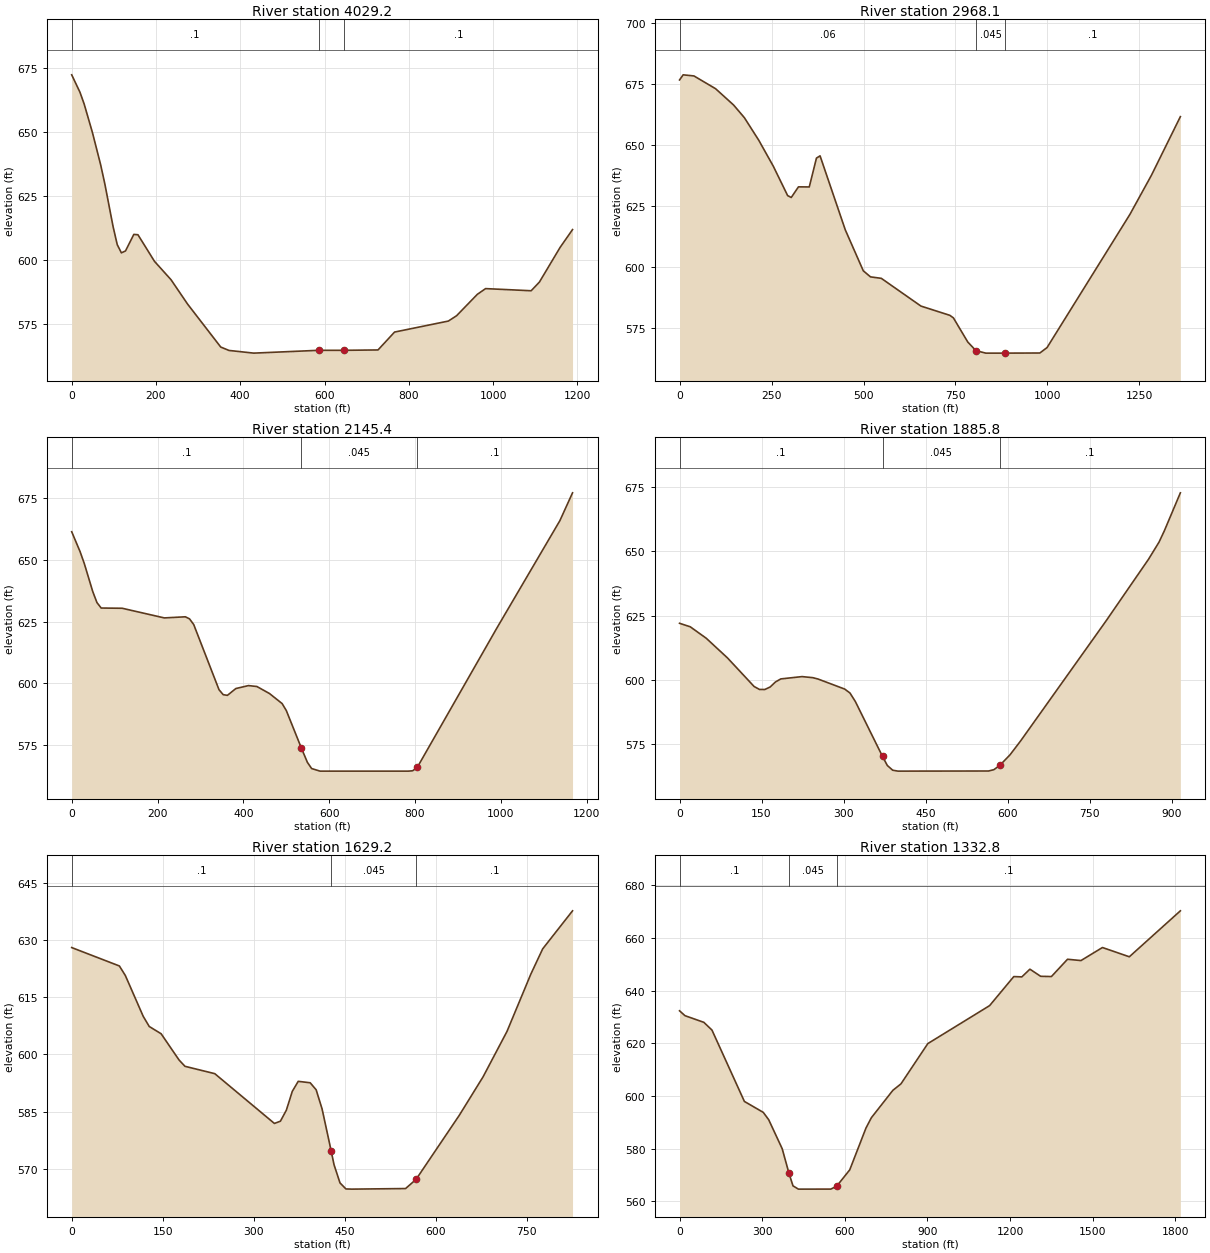
Type RM Length L Ch R = 1 ,4029.2  ,1060,1061,1062.1
XS GIS Cut Line= 2
     1721798.119      525964.145     1720982.655      525099.259
#Sta/Elev= 30
       0  672.24    19.6  665.44    29.5  660.87    49.1  649.75    68.8  637.03
    78.6  629.65    98.2  612.95   108.1  605.89   117.9  602.68   127.7  603.43
   147.4  609.88   157.2  609.76   196.5  599.36   235.8  592.17   275.1  582.65
   353.7  565.88   373.3  564.55   432.2   563.5   586.4   564.6   646.4   564.6
     727  564.74   766.3  571.73     894  576.03   913.6  578.13   962.8  586.48
   982.4  588.71  1090.5  587.87  1110.1  591.27  1159.2  604.81  1188.7  611.77
#Mann= 3 , 0 , 0
       0      .1       0   586.4    .045       0   646.4      .1       0
Bank Sta=586.4,646.4
XS Rating Curve= 0 ,0
Exp/Cntr=0.3,0.1

Type RM Length L Ch R = 1 ,2968.1  ,827.3,822.7,817.9
XS GIS Cut Line= 2
     1722809.689      525623.812     1721913.964      524598.799
#Sta/Elev= 30
       0  676.48     9.8  678.58    39.2  678.12    97.9   672.9   146.9  666.22
   176.3  661.01   215.4  651.77   254.6  641.22   293.8  629.12   303.6  628.34
   323.2   632.7   352.6  632.66   372.1  644.47   381.9   645.4   450.5  615.08
   499.4  598.32     519  595.83   548.4  595.23   656.1  583.87   734.5  580.09
   744.3  579.04   783.4  569.15   805.5565.6206   832.4   564.6   885.5   564.6
   979.3  564.65   998.9  566.89  1224.1  621.43  1282.9  637.55  1361.2  661.45
#Mann= 3 , 0 , 0
       0     .06       0   805.5    .045       0   885.5      .1       0
Bank Sta=805.5,885.5
XS Rating Curve= 0 ,0
Exp/Cntr=0.3,0.1

Type RM Length L Ch R = 1 ,2145.4  ,257.7,259.6,261.4
XS GIS Cut Line= 2
     1723266.853      524773.447     1722374.151       524021.53
#Sta/Elev= 30
       0   661.3    19.6  653.23    29.4  648.42      49  637.17    58.8  632.69
    68.7  630.48   117.7  630.39   215.8  626.49   264.8  626.94   274.6  626.11
   284.4   623.8   343.3  597.49   353.1  595.48   362.9  595.21   382.5  597.96
   411.9  599.15   431.6  598.78     461  595.94   490.4  591.88   500.2  589.05
   535.3573.8892   549.3  568.15   559.1  565.65   578.7   564.6   784.7   564.6
   794.5  564.74   805.3566.1004   990.6  622.32  1137.8  665.81  1167.2  677.02
#Mann= 3 , 0 , 0
       0      .1       0   535.3    .045       0   805.3      .1       0
Bank Sta=535.3,805.3
XS Rating Curve= 0 ,0
Exp/Cntr=0.3,0.1

Type RM Length L Ch R = 1 ,1885.8  ,256.6,256.6,256.6
XS GIS Cut Line= 2
      1723247.37      524456.711     1722584.515      523824.483
#Sta/Elev= 30
       0  622.06    19.5  620.71    48.7  616.27    87.7   608.6   136.4  597.49
   146.2  596.35   155.9  596.32   165.7   597.3   175.4  599.25   185.2  600.44
   224.1  601.34   243.6  600.93   253.4  600.39   302.1  596.49   311.8  594.94
   321.6  591.63   371.2  570.32     380   566.8   389.8  564.96   399.5   564.6
   565.2  564.65     575  565.17   586.2 566.937   604.2  570.88   623.7  576.31
   779.6  622.84   857.6   646.9     877  653.62   886.8  658.06     916  672.77
#Mann= 3 , 0 , 0
       0      .1       0   371.2    .045       0   586.2      .1       0
Bank Sta=371.2,586.2
XS Rating Curve= 0 ,0
Exp/Cntr=0.3,0.1

Type RM Length L Ch R = 1 ,1629.2  ,298.8,296.4,294
XS GIS Cut Line= 2
      1723443.57      524289.182     1722846.232      523719.444
#Sta/Elev= 30
       0  628.11    78.6  623.27    88.4  620.77   117.9  610.02   127.8  607.36
   147.4  605.45   176.9  598.56   186.7  596.89   235.8  594.96   334.1  581.87
     344  582.46   353.8  585.36   363.6  590.31   373.4  592.94   393.1  592.56
   402.9  590.72   412.7  585.68   427.6574.6935   432.4  571.02   442.2  566.24
     452  564.65   461.9   564.6   550.3  564.75   567.6  567.16   638.8     584
   678.1  594.14   717.4  606.04   756.7   621.1   776.3  627.77   825.5  637.77
#Mann= 3 , 0 , 0
       0      .1       0   427.6    .045       0   567.6      .1       0
Bank Sta=427.6,567.6
XS Rating Curve= 0 ,0
Exp/Cntr=0.3,0.1

Type RM Length L Ch R = 1 ,1332.8  ,623.4,700.8,761.3
XS GIS Cut Line= 3
     1723684.802      524053.259     1723121.296      523595.516
     1722043.932      523412.427
#Sta/Elev= 30
       0  632.36    19.6  630.51    88.3  627.97   117.7  625.04   235.5  597.92
   304.1  593.76   323.8  590.97   372.8  579.95   397.6570.5508     412  565.84
   431.7   564.6   549.4  564.61   570.6565.7094   618.1  571.93   676.9  587.78
   696.6  591.73   774.8  602.15     804  604.58   901.6  619.89    1126  634.32
  1213.9  645.36  1243.1  645.24  1272.4  648.17  1311.4  645.46  1350.5  645.37
    1409  651.94  1457.8  651.44  1535.8   656.4  1633.4  652.88  1818.8  670.34
#Mann= 3 , 0 , 0
       0      .1       0   397.6    .045       0   570.6      .1       0
Bank Sta=397.6,570.6
XS Rating Curve= 0 ,0
Exp/Cntr=0.3,0.1

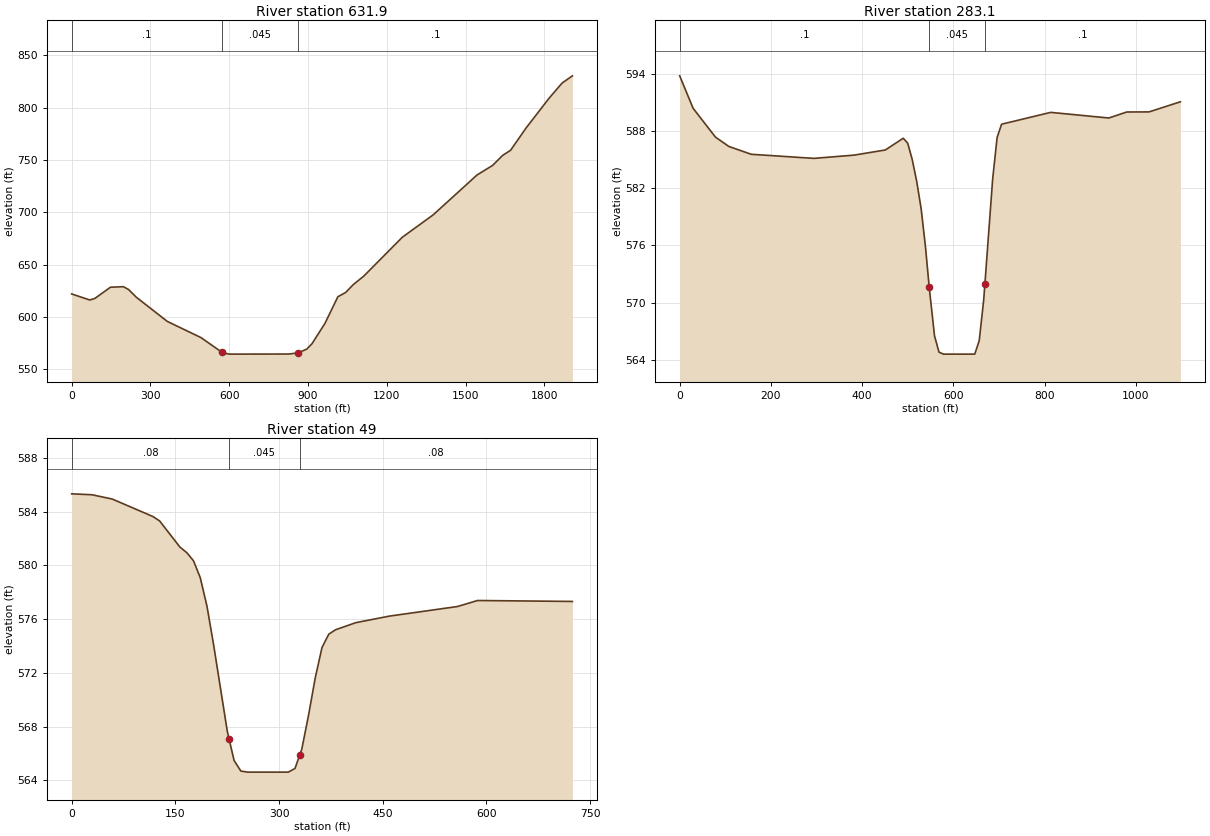
Type RM Length L Ch R = 1 ,631.9   ,402.8,348.9,311.8
XS GIS Cut Line= 3
     1723777.042      523928.205     1723647.787       522922.94
     1722596.899      522136.527
#Sta/Elev= 30
       0  622.09    68.9  616.32    88.6  617.87   147.6  628.52   196.8  629.03
   216.5  626.34     246  618.97   364.1  595.84     492  580.43   573.3566.1573
   600.2   564.6   826.6  564.68   863.3565.8135   895.5  569.49   915.1  574.58
   964.3  593.97  1013.5  619.44    1043  623.48  1072.4   631.1  1111.7  639.02
  1258.8  676.26  1376.6  697.71  1543.4  735.76  1602.3  744.85  1641.5   754.6
    1671  759.33  1729.8  780.56  1818.1  809.24  1867.2  823.57  1906.4  830.49
#Mann= 3 , 0 , 0
       0      .1       0   573.3    .045       0   863.3      .1       0
Bank Sta=573.3,863.3
XS Rating Curve= 0 ,0
Exp/Cntr=0.3,0.1

Type RM Length L Ch R = 1 ,283.1   ,234.5,234.1,233.7
XS GIS Cut Line= 2
     1724042.873      523678.349      1723910.02      522588.486
#Sta/Elev= 30
       0  593.76    29.4  590.36    78.4  587.34   107.8  586.36   156.8  585.54
   294.1  585.11   382.3  585.45   450.9  585.99   490.2  587.22     500   586.7
   509.8  585.01   519.6  582.73   529.4  579.86   539.2  575.72   547.2571.5812
   558.8  566.51   568.6  564.81   578.4   564.6     647   564.6   656.8  566.01
   666.6  570.27   669.2571.9123   686.2  582.91     696  587.29   705.8  588.69
   813.6  589.93   941.1  589.34   980.3  589.97  1029.3  589.98  1097.9  591.04
#Mann= 3 , 0 , 0
       0      .1       0   547.2    .045       0   669.2      .1       0
Bank Sta=547.2,669.2
XS Rating Curve= 0 ,0
Exp/Cntr=0.3,0.1

Type RM Length L Ch R = 1 ,49      ,45.5,49,52.4
XS GIS Cut Line= 2
     1724241.245      523346.261     1724144.154      522628.534
#Sta/Elev= 30
       0  585.34    29.4  585.27    58.7  584.95   117.4  583.65   127.2  583.32
   156.6  581.37   166.4  580.96   176.2  580.35     186  579.09   195.8  576.94
   205.5  574.02   225.1  567.64   227.7567.0643   234.9  565.47   244.7  564.68
   254.5   564.6   313.2   564.6     323  564.87   329.7565.8477   332.8   566.3
   342.6  568.83   352.3  571.62   362.1  573.89   371.9  574.88   381.7  575.21
   411.1  575.74     460  576.23   557.9  576.94   587.2  577.39   724.3  577.32
#Mann= 3 , 0 , 0
       0     .08       0   227.7    .045       0   329.7     .08       0
Bank Sta=227.7,329.7
XS Rating Curve= 0 ,0
Exp/Cntr=0.3,0.1

Chan Stop Cuts=-1
Use User Specified Reach Order=0
Composite Channel Slope=5